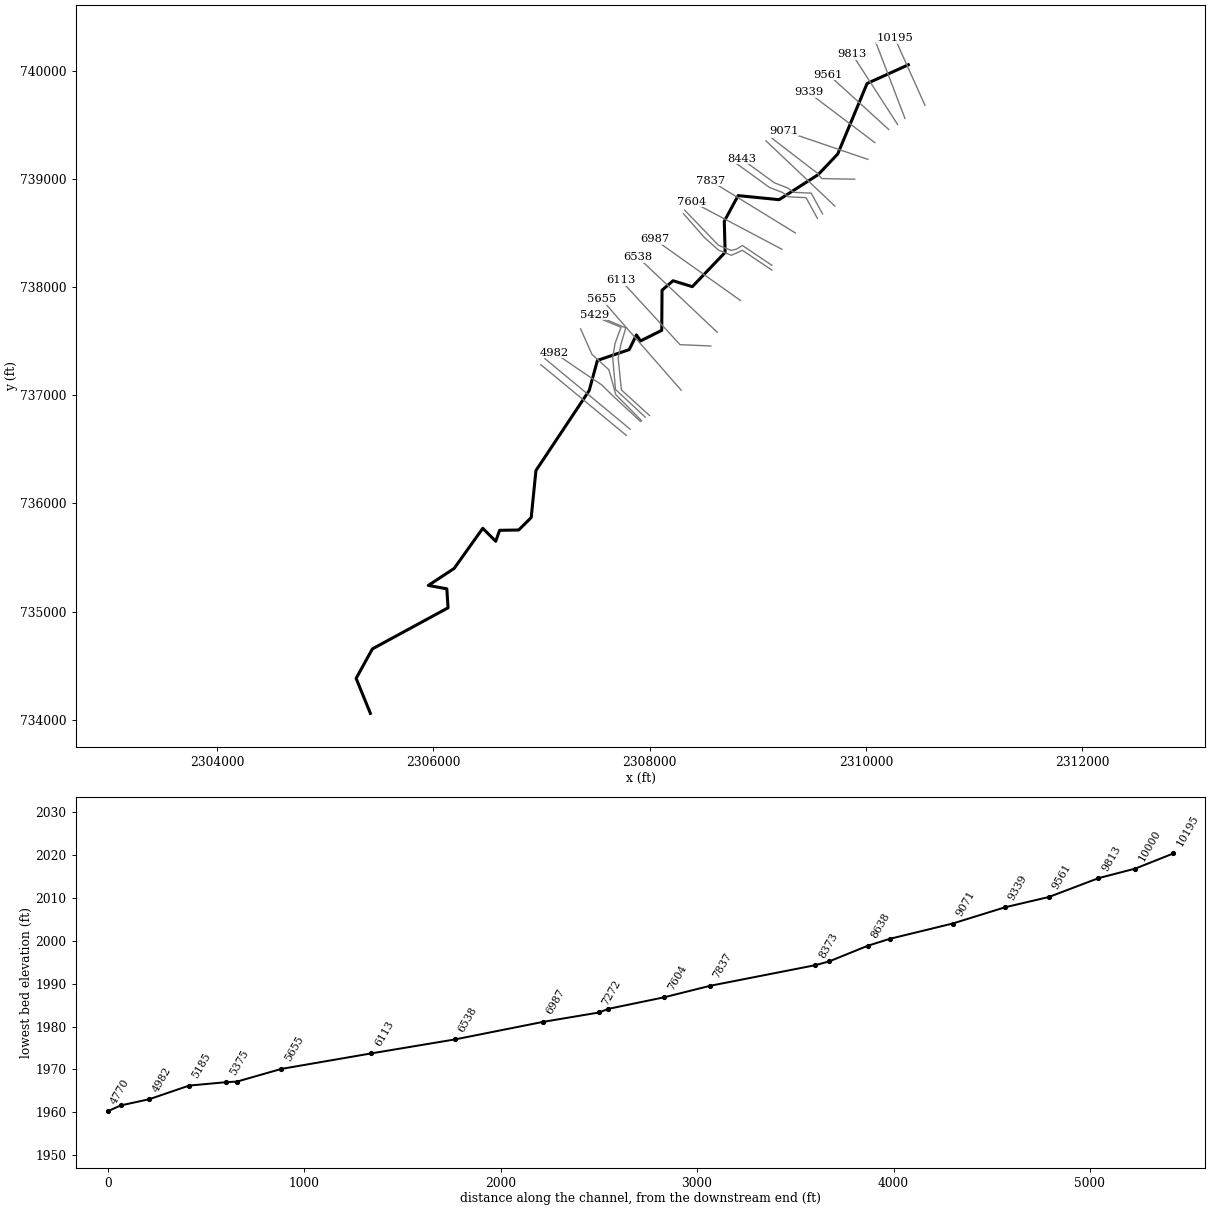
--- LAZYRN.prj (project) ---

Proj Title=LAZYRN
Current Plan=p01
Default Exp/Contr=0,0
English Units
Geom File=g01
Flow File=f01
Plan File=p01
BEGIN DESCRIPTION:
----------MODEL BY WOOD PLC 2022----------
AFH study
Randolph County, WV
HEC-RAS Version: RAS 6.2
Vertical Datum: NAVD88
Projection: NAD 1983 StatePlane West Virginia S FIPS 4702 (US Feet)
Terrain: 1-meter LIDAR (FEMA Region III 3DEP collected 2016-2018)
Land Use: 2019 NLCD
Hydrologic Method:
WV SIR2010-5033 regression equations
Additional Model Notes:
None
END DESCRIPTION:
DSS Export Rating Curves= 0
DSS Export Rating Curve Sorted= 0
DSS Export Volume Flow Curves= 0
DXF OffsetX= 0
DXF OffsetY= 0
DXF ScaleX= 0
DXF ScaleY= 0

--- LAZYRN.p01 (plan) ---

Plan Title=Floodplain
Program Version=6.20
Short Identifier=Floodplain
Geom File=g01
Flow File=f01
Subcritical Flow
K Sum by GR= 0
Std Step Tol= 0.01
Critical Tol= 0.01
Num of Std Step Trials= 20
Max Error Tol= 0.3
Flow Tol Ratio= 0.001
Split Flow NTrial= 30
Split Flow Tol= 0.02
Split Flow Ratio= 0.02
Log Output Level= 0
Friction Slope Method= 1
Unsteady Friction Slope Method= 2
Unsteady Bridges Friction Slope Method= 1
Parabolic Critical Depth
Global Vel Dist= 0 , 0 , 0
Global Log Level= 0
CheckData=True
Encroach Param=-1 ,0,0, 0
Mapping Interval=1HOUR
Computation Time Step Use Courant=        0
Computation Time Step Use Time Series=    0
Computation Time Step Count To Double=0
Computation Time Step Max Doubling=0
Computation Time Step Max Halving=0
Computation Time Step Residence Courant=0
Run HTab= 0
Run UNet= 0
Run Sediment= 0
Run PostProcess= 0
Run WQNet= 0
Run RASMapper=-1
UNET Theta= 0
UNET Theta Warmup= 0
UNET ZTol= 0
UNET ZSATol= 0
UNET MxIter= 0
UNET Max Iter WO Improvement= 0
UNET MaxInSteps= 0
UNET DtIC= 0
UNET DtMin= 0
UNET MaxCRTS= 0
UNET WFStab= 0
UNET SFStab= 0
UNET WFX= 1
UNET SFX= 1
UNET Gravity=32.174
UNET 1D Methodology=Finite Difference
UNET DSS MLevel= 1
UNET Pardiso=0
UNET DZMax Abort= 0
UNET Use Existing IB Tables= 0
UNET Froude Reduction=False
UNET Froude Limit= 0
UNET Froude Power= 0
UNET D1 Cores= 0
UNET WindReference=Eulerian
UNET WindDragFormulation=Hsu (1988)
UNET D2 Coriolis=0
UNET D2 Cores= 0
UNET D2 Theta= 1
UNET D2 Theta Warmup= 1
UNET D2 Z Tol= 0.01
UNET D2 Volume Tol= 0.01
UNET D2 Max Iterations= 20
UNET D2 Equation= 0
UNET D2 RampUpFraction=0.1
UNET D2 TimeSlices= 1
UNET D2 Turbulence Formulation=Non-Conservative (original)
UNET D2 Eddy Viscosity=0.3
UNET D2 Transverse Eddy Viscosity=0.1
UNET D2 Smagorinsky Mixing=0
UNET D2 BCVolumeCheck=0
UNET D2 Cores=0
UNET D2 SolverType=PARDISO (Direct)
UNET D2 Minimum Iterations= 2147483647
UNET D2 Maximum Iterations= 2147483647
UNET D2 Restart Number= 10
UNET D2 Relaxation Coeff=1.3
UNET D2 SOR Precondition Iterations= 10
UNET D2 ILUT Maximum Fill= 8
UNET D2 ILUT Tolerance=1E-08
UNET D1D2 MaxIter= 0
UNET D1D2 ZTol=0.01
UNET D1D2 QTol=0.1
UNET D1D2 MinQTol=1
Write IC File= 0
Write IC File at Fixed DateTime=0
Write IC File at Sim End=0
Echo Input=False
Echo Parameters=False
Echo Output=False
Write Detailed= 0
HDF Write Warmup=0
HDF Write Time Slices=0
HDF Flush=0
HDF Compression= 1
HDF Chunk Size= 1
HDF Spatial Parts= 1
HDF Use Max Rows=0
HDF Fixed Rows= 1
Calibration Method= 0
Calibration Iterations= 20
Calibration Max Change=0.05
Calibration Tolerance=0.2
Calibration Maximum=1.5
Calibration Minimum=0.5
Calibration Optimization Method= 1
WQ AD Non Conservative
WQ ULTIMATE=-1
WQ Max Comp Step=1HOUR
WQ Output Interval=15MIN
WQ Output Selected Increments= 0
WQ Output face flow=0
WQ Output face velocity=0
WQ Output face area=0
WQ Output face dispersion=0
WQ Output cell volume=0
WQ Output cell surface area=0
WQ Output cell continuity=0
WQ Output cumulative cell continuity=0
WQ Output face conc=0
WQ Output face dconc_dx=0
WQ Output face courant=0
WQ Output face peclet=0
WQ Output face adv mass=0
WQ Output face disp mass=0
WQ Output cell mass=0
WQ Output cell source sink temp=0
WQ Output nsm pathways=0
WQ Output nsm derived pathways=0
WQ Create Restart=0
WQ Fixed Restart=0
WQ System Summary=0
WQ Write To DSS=0
Sorting and Armoring Iterations= 10
XS Update Threshold= 0.02
Bed Roughness Predictor= 0
Hydraulics Update Threshold= 0.02
Energy Slope Method= 1
Volume Change Method= 1
Sediment Retention Method= 0
Sediment TS Multiplier= 1
Warm Up Method= 0
XS Weighting Method= 0
Number of US Weighted Cross Sections= 1
Number of DS Weighted Cross Sections= 1
Upstream XS Weight=0
Main XS Weight=1
Downstream XS Weight=0
Number of DS XS's Weighted with US Boundary= 1
Upstream Boundary Weight= 1
Weight of XSs Associated with US Boundary= 0
Number of US XS's Weighted with DS Boundary= 1
Downstream Boundary Weight= 0.5
Weight of XSs Associated with DS Boundary= 0.5
Percentile Method= 0
Sediment Output Level= 3
Mass or Volume Output= 0
Output Increment Type= 1
Profile and TS Output Increment= 1
Transport Output Increment 1
XS Output Flag= 0
XS Output Increment= 10
Read HDF5 Sediment Hotstart= 0
Sediment Hotstart Type= 0
Write Gradation File= 0
Read Gradation Hotstart= 0
Write HDF5 File= 1
Write Binary Output= 1
Write DSS Sediment File= 0
DSS Sediment Output Type= 1
SV Curve= 0
Specific Gage Flag= 0
Subcell Erosion Methods= 0
Subcell Deposition Methods= 0
Advection Scheme= 1
Matrix Solver= 0
Implicit Weighting Factor= 1
Maximum Outer Loop Convergence Iterations= 5
Convergence Maximum Absolute= 0.001
Convergence RMSE= 0.0001
Grain Fractions Max Abs Error= 0.001
Max Subgrid Regions= 1
Max Subgrid Length Scale= 3.402823E+38
Initial Layer Thickness= 3.402823E+38
Min Layer Thickness= 3.402823E+38
Max Layer Thickness= 3.402823E+38
Number of Layers= 5

--- LAZYRN.f01 (steady flow) ---

Flow Title=Flow
Program Version=4.00
Number of Profiles=1
Profile Names=P100yr
River Rch & RM=LAZYRN,Main,10195
     375
River Rch & RM=LAZYRN,Main,5655
     531
River Rch & RM=LAZYRN,Main,3899
     592
Boundary for River Rch & Prof#=LAZYRN,Main      ,1
Up Type=0
Dn Type=3
Dn Slope=0.004292

--- LAZYRN.g01 (geometry) ---

Geom Title=Geometry
Program Version=6.20

River Reach=LAZYRN          ,Main
Reach XY= 30
     2310391.097      740057.833     2310009.543      739884.656
     2309738.144      739232.449     2309556.764      739041.043
        2309196.      738810.0972308817.63733673738847.805663266
     2308689.779      738611.059     2308697.374      738322.431
     2308394.423      738005.373     2308215.849      738060.278
      2308114.46      737972.778     2308111.468      737601.374
     2307915.201      737503.517     2307877.592       737559.17
     2307811.186      737423.327     2307517.035      737323.197
     2307441.039      737044.442     2306948.938      736304.685
     2306905.062      735869.627     2306789.216      735754.685
     2306612.773      735751.652     2306577.258      735650.288
     2306457.272       735770.31     2306192.862       735399.13
     2305954.147      735242.012     2306125.218      735210.458
      2306136.33      735034.763     2305437.163      734654.902
     2305286.777      734381.962     2305418.516      734058.392

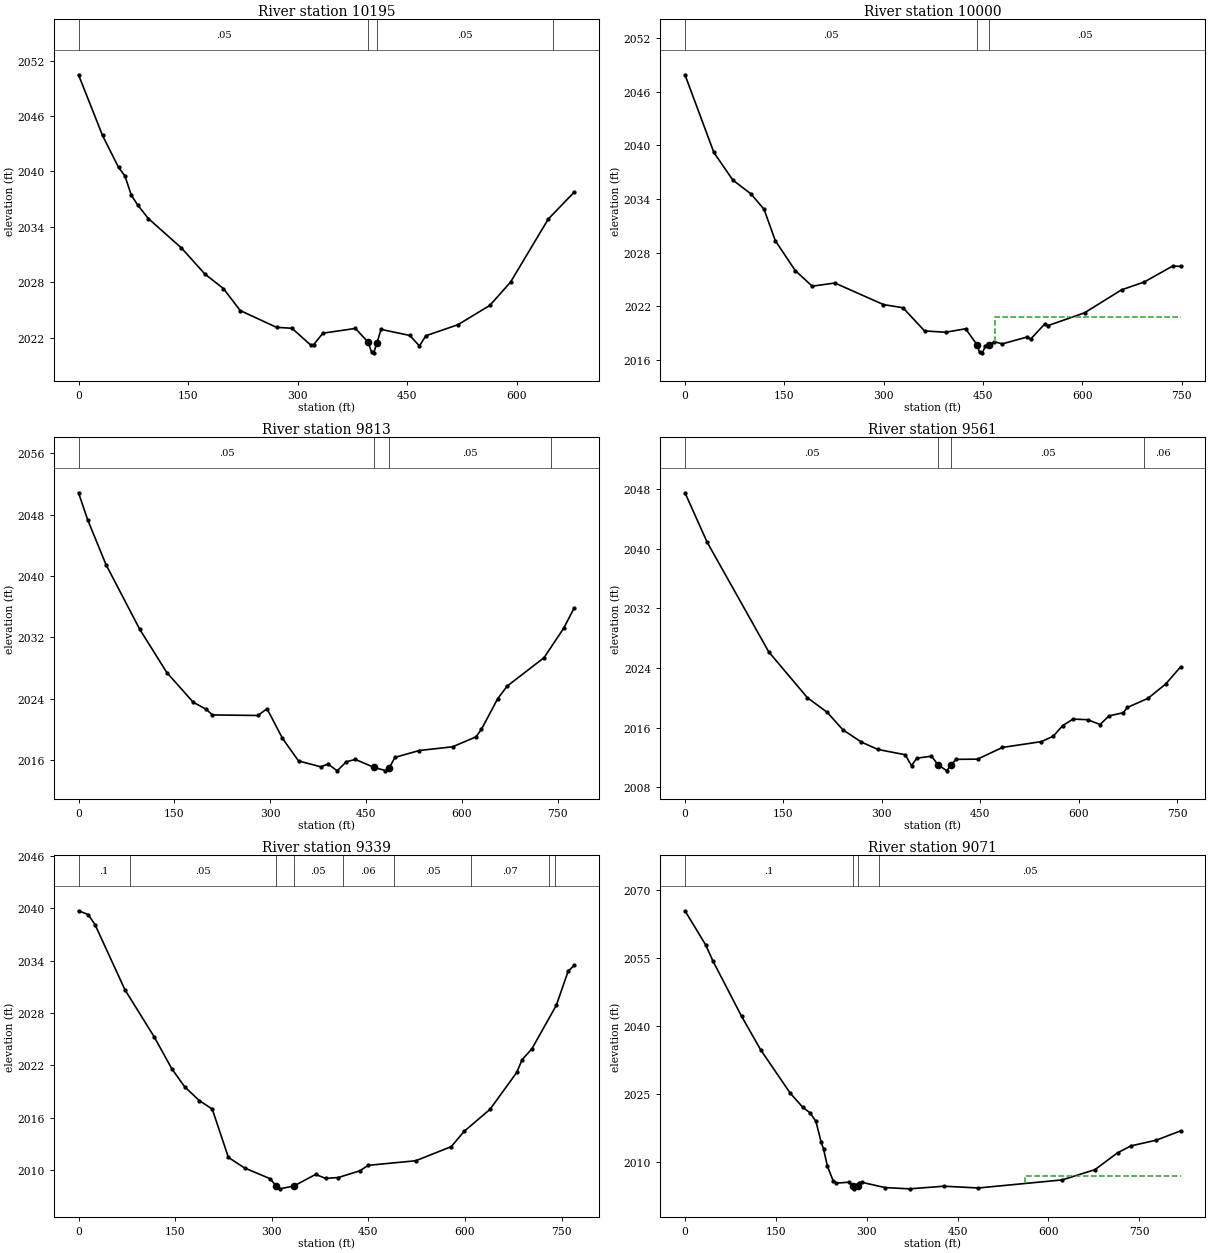
Type RM Length L Ch R = 1 ,10195   ,194.6,194.6,194
XS GIS Cut Line= 2
2310544.59209859739683.1886262542310266.63603718740302.517908718
#Sta/Elev= 30
       0 2050.46    32.9 2043.89    54.8 2040.44    63.6  2039.5    72.3 2037.42
    81.1 2036.36    95.6  2034.9     141 2031.71   173.2 2028.88   198.5 2027.32
   221.4 2024.94   271.2 2023.12   292.3 2023.02   317.9 2021.21   322.2 2021.26
   334.7 2022.49   379.2    2023   396.8  2021.5   401.3 2020.44   404.3 2020.36
   408.8 2021.46   414.3  2022.9   453.8 2022.24   466.9  2021.1   475.7 2022.21
   519.5  2023.4   563.4  2025.5   591.7 2028.02   643.4 2034.85   678.8 2037.75
#Mann= 4, -1 ,  0
       0    0.05       0   396.8   0.045       0   408.8    0.05       0
     650    0.06       0
Bank Sta=396.8,408.8
XS Rating Curve= 0 ,0
Exp/Cntr(USF)=0,0
Exp/Cntr=0.3,0.1

Type RM Length L Ch R = 1 ,10000   ,185.4,187.2,189.2
XS GIS Cut Line= 2
2310359.73782474739561.7515120462310092.57617348 740260.68956938
#Sta/Elev= 30
       0 2047.88    43.6  2039.2    72.2 2036.12    99.6 2034.57   119.3 2032.86
   136.4 2029.34   166.5    2026   192.1 2024.26   226.3 2024.61   299.7  2022.2
   329.1 2021.85   361.7 2019.26   393.4 2019.11   423.7  2019.5  441.552017.643
   444.7 2016.85     449 2016.81   453.3 2017.54  459.28 2017.65     467 2018.06
     479 2017.81   516.6 2018.58   521.8 2018.34   543.2 2020.04   547.5 2019.84
   603.2 2021.28   659.1 2023.85   693.2 2024.72   736.6 2026.52   748.3 2026.47
#Mann= 3, -1 ,  0
       0    0.05       0  441.55   0.045       0  459.28    0.05       0
#XS Ineff= 2 , 0
                          467.64         2020.79
Permanent Ineff=
       F       F
Bank Sta=441.55,459.28
XS Rating Curve= 0 ,0
Exp/Cntr(USF)=0,0
Exp/Cntr=0.3,0.1

Type RM Length L Ch R = 1 ,9813    ,247.4,252.1,253.7
XS GIS Cut Line= 2
2310292.27276129739505.0808587482309871.29076537740156.793371668
#Sta/Elev= 30
       0 2050.85    14.4 2047.31      43 2041.49    95.6 2033.08   138.2 2027.41
   179.5 2023.54   199.8 2022.62   209.6 2021.88   280.8 2021.81   295.1 2022.69
   319.2 2018.84   344.4 2015.88   379.1 2015.12   390.7 2015.47   404.9 2014.59
   419.2 2015.78   433.5 2016.07     463 2015.03   480.4 2014.63   486.7 2015.02
   495.4 2016.35   533.5 2017.24   585.8 2017.73   622.2 2019.02   630.8 2020.02
   656.3 2024.02   671.3 2025.66   728.7 2029.34   759.5 2033.19   775.9 2035.83
#Mann= 4, -1 ,  0
       0    0.05       0     463   0.045       0   486.7    0.05       0
     740    0.06       0
Bank Sta=463,486.7
XS Rating Curve= 0 ,0
Exp/Cntr(USF)=0,0
Exp/Cntr=0.3,0.1

Type RM Length L Ch R = 1 ,9561    ,220.2,221.7,220.2
XS GIS Cut Line= 2
2310209.96538388739459.2046156032309651.35465852 739967.89119401
#Sta/Elev= 30
       0 2047.49    33.8 2040.86   127.7 2026.15   186.7    2020   216.8 2018.05
   240.6 2015.71   268.8 2014.06     294 2013.07   335.6 2012.36   345.3 2010.89
   353.4  2011.9   375.7 2012.16  385.682011.027   399.1  2010.2  405.652011.013
   413.2 2011.74     446 2011.77   483.9 2013.34   543.4 2014.12   561.4 2014.85
   575.9 2016.28   591.6 2017.14   613.7 2017.06   632.7 2016.41   646.2 2017.56
   668.1    2018   674.3  2018.7   705.7 2019.92   732.8 2021.85   755.5 2024.15
#Mann= 4, -1 ,  0
       0    0.05       0  385.68   0.045       0  405.65    0.05       0
     700    0.06       0
Bank Sta=385.68,405.65
XS Rating Curve= 0 ,0
Exp/Cntr(USF)=0,0
Exp/Cntr=0.3,0.1

Type RM Length L Ch R = 1 ,9339    ,263.9,268.5,274
XS GIS Cut Line= 2
2310081.78176333739337.7675013942309467.84968594739801.927137925
#Sta/Elev= 30
       0 2039.72      15 2039.29    25.6 2038.14      72 2030.67   117.8 2025.22
   144.9 2021.59   164.8 2019.53   187.6 2017.94   207.6 2016.98   232.7 2011.43
   257.9 2010.21   297.9 2008.97   306.3 2008.18   312.9 2007.82   334.7 2008.16
   368.1 2009.47   383.7 2009.02   403.4 2009.12   436.8 2009.89     450 2010.52
   523.5 2011.04   578.7 2012.66   598.7 2014.41   638.9 2016.94   680.4 2021.17
   688.8 2022.64   704.1  2023.9   741.9 2028.88   760.3  2032.8   769.6 2033.45
#Mann= 9, -1 ,  0
       0     0.1       0      80    0.05       0   306.3   0.045       0
   334.7    0.05       0     410    0.06       0     490    0.05       0
     610    0.07       0     730     0.1       0     740    0.06       0
Bank Sta=306.3,334.7
XS Rating Curve= 0 ,0
Exp/Cntr(USF)=0,0
Exp/Cntr=0.3,0.1

Type RM Length L Ch R = 1 ,9071    ,321.9,320.3,316
XS GIS Cut Line= 2
2310016.74715871739183.0529001552309242.24823032739447.515948876
#Sta/Elev= 30
       0 2065.36    34.4 2057.78    46.2 2054.27    93.6 2042.04     125 2034.67
   173.9  2025.1   194.3 2022.03   206.9 2020.74   216.2  2018.9   224.6 2014.44
   228.9 2012.73   235.3 2008.94   244.7 2005.78     250 2005.26   271.1 2005.49
  277.04 2004.58   279.6 2004.02  284.98 2004.58     288 2005.38   292.3 2005.44
   330.3 2004.29   370.8 2004.01   427.4 2004.59   484.2  2004.2   622.8 2005.98
   676.9 2008.24   714.2 2011.95   736.1 2013.48   778.3 2014.75   818.4 2016.81
#Mann= 4, -1 ,  0
       0     0.1       0  277.04   0.045       0  284.98     0.1       0
     320    0.05       0
#XS Ineff= 2 , 0
                          561.21         2006.91
Permanent Ineff=
       F       F
Bank Sta=277.04,284.98
XS Rating Curve= 0 ,0
Exp/Cntr(USF)=0,0
Exp/Cntr=0.3,0.1

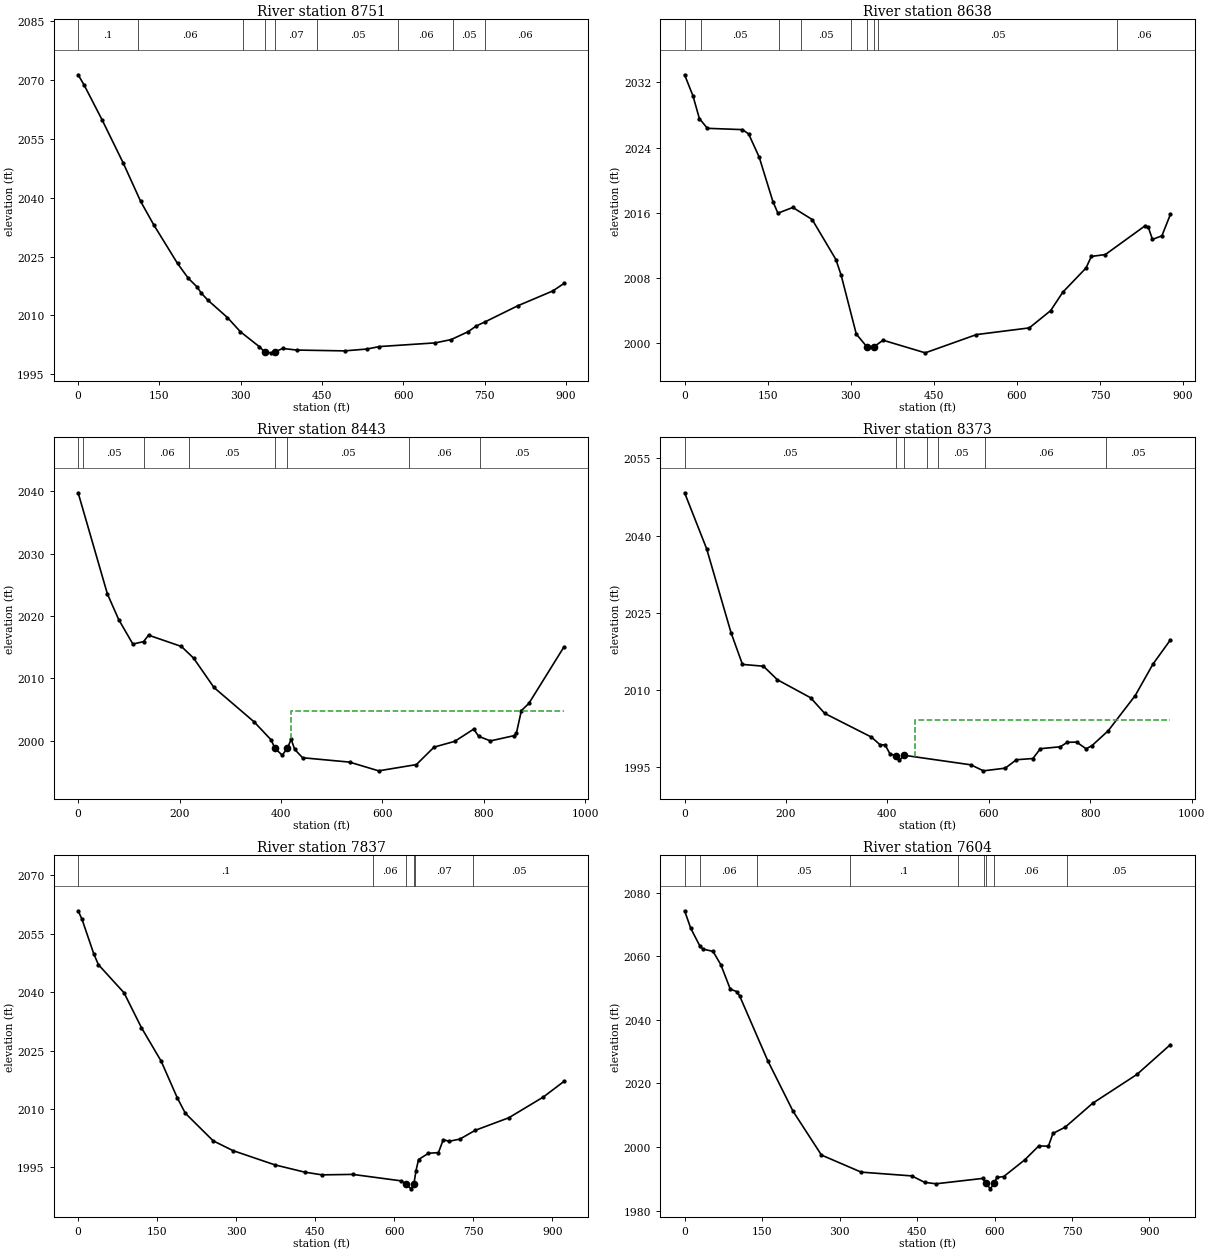
Type RM Length L Ch R = 1 ,8751    ,111,112.2,112.4
XS GIS Cut Line= 6
2309895.57818821738999.3966902332309592.03824127739005.234085273
2309577.55710506739020.4773865522309545.54617237739060.109969877
2309516.58389994739080.6884266032309132.07093888739376.782488705
#Sta/Elev= 30
       0 2071.33    11.4 2068.62    44.3 2059.81    83.4 2048.77   115.4 2039.04
   139.4  2033.1   183.4 2023.23   203.4 2019.43   219.4 2017.26   227.4 2015.64
   239.4 2013.87   275.5 2009.44   299.5 2005.81   334.6 2001.99  344.43 2000.64
   356.4 2000.44   363.1 2000.64   377.2 2001.56   403.1 2001.15   491.6 2000.94
   532.8 2001.41   556.1 2002.04     659 2002.98   688.4 2003.82   719.8 2005.84
   734.7 2007.29   751.1 2008.35     811 2012.42   876.1 2016.23   896.4 2018.12
#Mann= 9, -1 ,  0
       0     0.1       0     110    0.06       0   303.6    0.07       0
  344.43   0.045       0   363.1    0.07       0   441.1    0.05       0
   591.1    0.06       0   691.1    0.05       0   751.1    0.06       0
Bank Sta=344.43,363.1
XS Rating Curve= 0 ,0
Exp/Cntr(USF)=0,0
Exp/Cntr=0.3,0.1

Type RM Length L Ch R = 1 ,8638    ,195.4,195.4,195.4
BEGIN DESCRIPTION:
Structure XS 4
END DESCRIPTION:
XS GIS Cut Line= 2
2309712.07321563738750.8214493862309075.20301667739353.959116622
#Sta/Elev= 30
       0 2032.94    15.1 2030.35    26.7 2027.56    41.2 2026.37   104.5 2026.21
   115.6 2025.68   134.6 2022.85   159.6 2017.35   168.5 2015.96   195.4 2016.66
   230.3 2015.18   273.2 2010.27   282.7 2008.34     310 2001.12   329.21999.558
  342.341999.585   358.3 2000.37   434.5 1998.82     527 2001.06   622.4 2001.88
   660.9    2004     683 2006.27   724.8 2009.23   734.4 2010.65   759.7 2010.88
   831.7 2014.42   837.2 2014.24   844.8 2012.74   861.8 2013.18   877.1  2015.8
#Mann= 9, -1 ,  0
       0     0.1       0      30    0.05       0     170    0.06       0
     210    0.05       0     300     0.1       0   329.2   0.045       0
  342.34     0.1       0     350    0.05       0     780    0.06       0
Bank Sta=329.2,342.34
XS Rating Curve= 0 ,0
Exp/Cntr(USF)=0,0
Exp/Cntr=0.5,0.3

Type RM Length L Ch R = 1 ,8443    ,70.2,70.2,70.2
BEGIN DESCRIPTION:
Structure XS 3 12.9ft
END DESCRIPTION:
XS GIS Cut Line= 6
2309598.19079321738678.6096455122309492.73399366738870.810594912
2309331.61365927738877.892807412 2309276.2640791738917.983958695
2309152.78779362 738966.42046367 2308848.2526561739187.739604315
#Sta/Elev= 30
       0 2039.77    57.7 2023.55      80 2019.44   107.9 2015.52   128.9  2015.9
   138.9 2016.94   203.7 2015.13   227.8 2013.25   267.8 2008.56   347.2 2003.03
   380.5 2000.16   388.2 1998.79   402.5  1997.7  412.411998.793   420.2 2000.24
     427 1998.64   442.6 1997.29   535.2 1996.59   592.6 1995.19     667 1996.19
   701.9 1998.99   742.7 1999.92   780.1 2001.88     790 2000.72   813.1 1999.99
   859.2 2000.82   864.2 2001.18   874.1 2004.84   888.9    2006     958 2015.04
#Mann= 8, -1 ,  0
       0     0.1       0      10    0.05       0     130    0.06       0
  219.23    0.05       0   388.2   0.045       0  412.41    0.05       0
  651.55    0.06       0  791.55    0.05       0
#XS Ineff= 2 , 0
                          420.22         2004.83
Permanent Ineff=
       F       F
Bank Sta=388.2,412.41
XS Rating Curve= 0 ,0
Exp/Cntr(USF)=0,0
Exp/Cntr=0.3,0.1

Type RM Length L Ch R = 1 ,8373    ,528.2,536.2,531.1
BEGIN DESCRIPTION:
Structure XS 2 13.2ft 4.4
END DESCRIPTION:
XS GIS Cut Line= 6
2309550.74125149738636.7731511262309445.28445194738828.974100526
2309284.16411755738836.0563130262309228.81453739738876.147464309
 2309105.3382519738924.5839692842308800.80311438739145.903109929
#Sta/Elev= 30
       0 2048.31    43.4 2037.45    91.7  2021.1   114.1 2014.98   155.4 2014.63
     183    2012   248.4 2008.51   276.4 2005.46   368.5 2000.86   385.4 1999.38
   395.6 1999.34   405.2 1997.56   416.5 1997.27   423.3 1996.32   432.9 1997.33
   564.5 1995.48   589.4 1994.31   632.4 1994.83   654.4 1996.47   686.8  1996.7
   701.7 1998.61   741.2 1998.99   754.6 1999.85   773.1 1999.89   791.9 1998.59
   803.3  1999.2   835.2 2002.07   888.7 2008.93   923.6 2015.03     958 2019.73
#Mann= 7, -1 ,  0
       0    0.05       0   416.5   0.045       0   432.9    0.05       0
  478.85     0.1       0  499.48    0.05       0  591.55    0.06       0
  831.55    0.05       0
#XS Ineff= 2 , 0
                          454.87         2004.17
Permanent Ineff=
       F       F
Bank Sta=416.5,432.9
XS Rating Curve= 0 ,0
Exp/Cntr(USF)=0,0
Exp/Cntr=0.5,0.3

Type RM Length L Ch R = 1 ,7837    ,232.2,232.9,233.2
BEGIN DESCRIPTION:
Structure XS 1
END DESCRIPTION:
XS GIS Cut Line= 2
2309346.41257173738502.5500158922308561.11923318738985.599870189
#Sta/Elev= 30
       0 2060.92     7.3 2058.75    29.7 2049.85    38.4 2047.09    87.2 2039.84
     120 2030.93   157.6 2022.29   188.2 2012.86   203.5 2008.91   256.2 2001.84
   293.8 1999.32   373.6 1995.65     430 1993.79   462.9 1993.09   521.1 1993.21
   613.1 1991.55   622.5 1990.76   631.9  1989.5   637.4 1990.86   641.3 1994.17
   646.1 1997.02   664.8 1998.63   683.9 1998.81     693 2002.11   704.3 2001.72
   724.6 2002.28   753.7 2004.53   817.7 2007.77     883 2013.09     922 2017.08
#Mann= 6, -1 ,  0
       0     0.1       0     560    0.06       0   622.5   0.045       0
   637.4    0.06       0     640    0.07       0     750    0.05       0
Bank Sta=622.5,637.4
XS Rating Curve= 0 ,0
Exp/Cntr(USF)=0,0
Exp/Cntr=0.3,0.1

Type RM Length L Ch R = 1 ,7604    ,283.7,286.3,286.5
BEGIN DESCRIPTION:
Structure XS 4
END DESCRIPTION:
XS GIS Cut Line= 2
2309222.27685499738351.4282737662308391.10727329738791.300487455
#Sta/Elev= 30
       0 2074.37    11.7 2068.93    29.5 2063.28    35.4 2062.33    55.1 2061.57
    70.3 2057.33    88.4 2049.71   100.5 2048.95   106.4 2047.62   160.8 2027.23
     210 2011.24   264.9 1997.47   341.8 1992.09   439.9  1990.9   464.5 1988.88
   486.6 1988.42     577 1990.11   582.9  1988.7   591.8 1986.83   599.8 1988.69
   604.3  1990.4   617.9 1990.71   658.6 1995.97   685.7 2000.35   704.2 2000.24
   713.1 2004.27   736.8 2006.25   789.8 2013.75   875.6 2022.84   940.4 2032.22
#Mann= 9, -1 ,  0
       0     0.1       0      30    0.06       0     140    0.05       0
     320     0.1       0     530    0.05       0     580    0.06       0
   582.9   0.045       0   599.8    0.06       0     740    0.05       0
Bank Sta=582.9,599.8
XS Rating Curve= 0 ,0
Exp/Cntr(USF)=0,0
Exp/Cntr=0.3,0.1

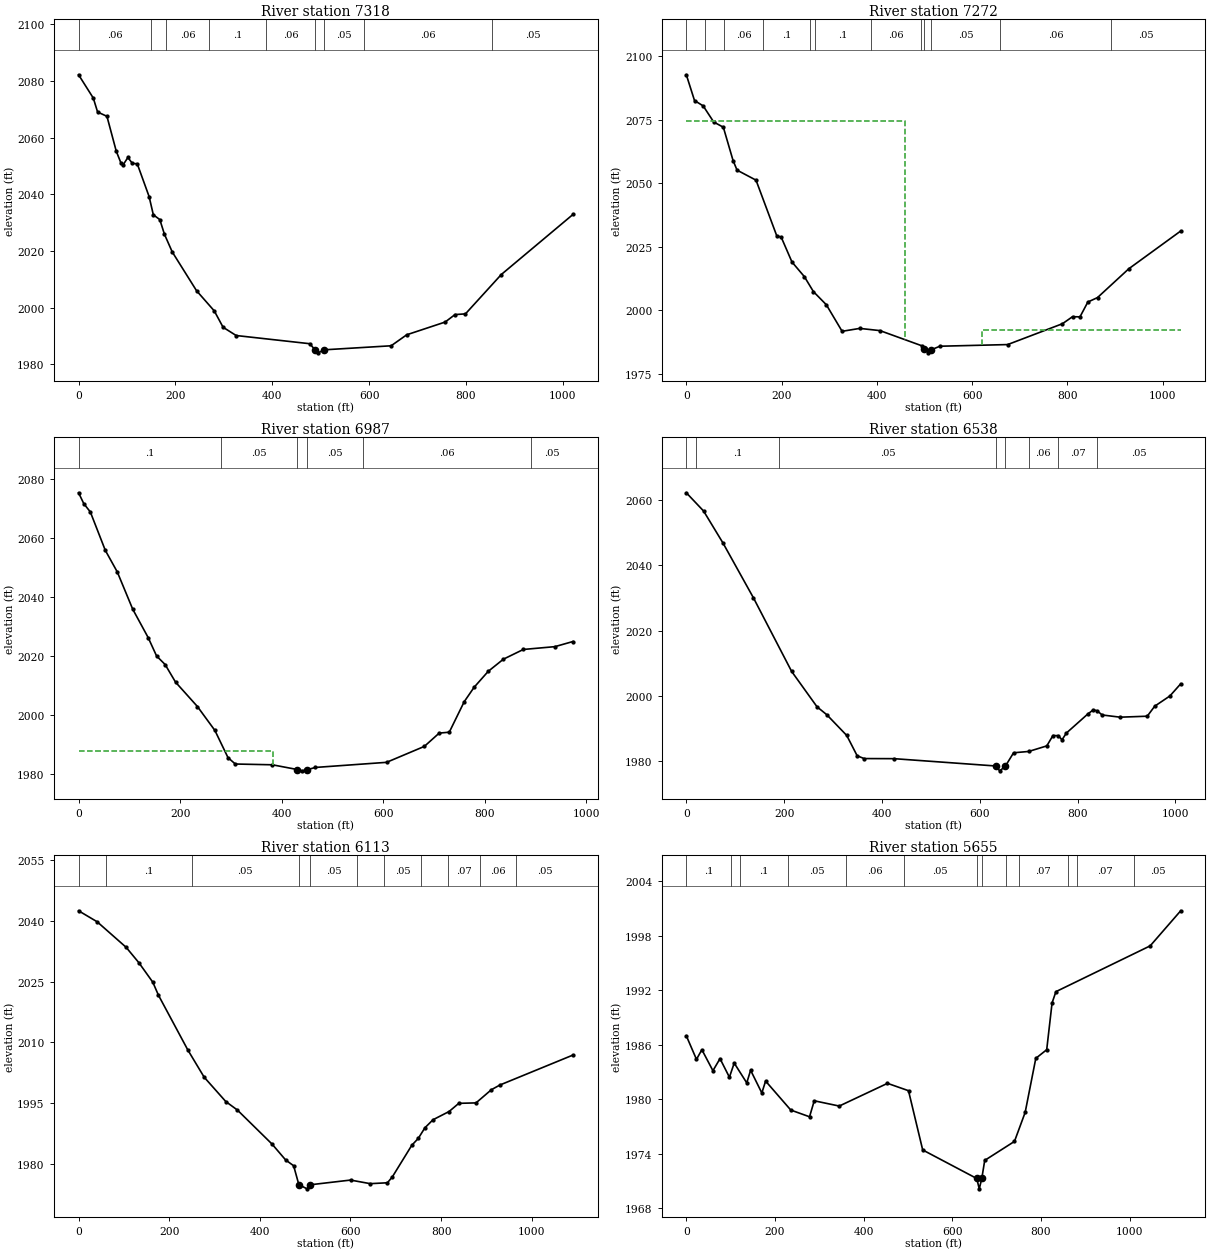
Type RM Length L Ch R = 1 ,7318    ,43.8,45.5,45.7
BEGIN DESCRIPTION:
Structure XS 3
END DESCRIPTION:
XS GIS Cut Line= 6
2309128.77362186738203.5625204362308856.55887016738386.567663429
2308804.17673588738353.149421113 2308754.2296558738340.577063518
2308636.55985306738387.7000454522308323.17194991738713.481820481
#Sta/Elev= 30
       0 2082.22    30.4    2074    39.3 2069.08    58.6 2067.56    77.8 2055.28
    87.5  2051.1    92.3 2050.53   101.9 2053.04   111.1 2050.95   121.2 2050.81
   145.7 2039.24   154.4 2032.82   167.8 2031.12   177.4 2025.93   193.5  2019.7
   243.7 2006.02   280.3  1998.9   298.5 1993.13   325.5 1990.22   477.6 1987.33
   488.5 1985.14   494.5 1984.11   507.5 1985.18   645.6  1986.6   677.8 1990.48
   757.1 1994.97   777.5 1997.61   799.1 1997.86   873.1 2011.74  1021.1 2032.93
#Mann= 9, -1 ,  0
       0    0.06       0     150     0.1       0     180    0.06       0
     270     0.1       0  388.01    0.06       0   488.5   0.045       0
   507.5    0.05       0  588.85    0.06       0  854.41    0.05       0
Bank Sta=488.5,507.5
XS Rating Curve= 0 ,0
Exp/Cntr(USF)=0,0
Exp/Cntr=0.3,0.1

Type RM Length L Ch R = 1 ,7272    ,286.6,285.4,284
BEGIN DESCRIPTION:
Structure XS 2
END DESCRIPTION:
XS GIS Cut Line= 6
2309129.55482911738158.7202790522308857.34007742738341.725422045
2308755.01086305738295.7348221342308637.34106031738342.857804068
2308507.85915931738458.3504054392308312.69166731 738679.90106895
#Sta/Elev= 30
       0 2092.62    17.2 2082.49    35.4 2080.38    57.5 2074.05    77.7 2071.99
    98.1 2058.91   106.5 2055.12   146.3 2051.18   189.6 2029.41   199.3 2028.71
   221.8 2018.98   247.8 2013.24   266.8 2007.35   293.9 2002.19     327 1991.75
     364 1992.89   406.5 1992.02   495.3 1985.99   499.5 1984.66   508.2 1983.28
   514.5 1984.51   532.2 1985.88   674.5 1986.53   789.5 1994.73   810.6 1997.49
   826.3 1997.43   842.8 2003.26   863.1 2005.01   928.7 2016.33  1037.7 2031.18
#Mann= 12, -1 ,  0
       0    0.06       0      40     0.1       0      80    0.06       0
     160     0.1       0     260    0.06       0     270     0.1       0
  388.01    0.06       0  491.65    0.05       0   499.5   0.045       0
   514.5    0.05       0  658.85    0.06       0  892.35    0.05       0
#XS Ineff= 2 , 0
          457.99 2074.38  619.91         1992.16
Permanent Ineff=
       F       F
Bank Sta=499.5,514.5
XS Rating Curve= 0 ,0
Exp/Cntr(USF)=0,0
Exp/Cntr=0.3,0.1

Type RM Length L Ch R = 1 ,6987    ,436.8,448.4,441
BEGIN DESCRIPTION:
Structure XS 1
END DESCRIPTION:
XS GIS Cut Line= 2
2308839.07529459737877.8235283522308045.68614843738441.831458788
#Sta/Elev= 30
       0 2075.29    10.2 2071.63    23.2 2068.78    52.6  2055.8    76.2 2048.48
   106.6 2035.86     137 2026.24   153.6    2020   170.4 2017.11   190.9 2011.15
     234 2002.88   268.4 1994.78   294.2 1985.57   308.6  1983.4   381.5 1983.14
   430.5 1981.54   440.3 1981.09   449.1 1981.43   466.3 1982.24   606.4 1983.97
   680.8 1989.37   710.1 1993.88   729.9 1994.18   759.3 2004.51   778.9 2009.42
   806.6  2014.8   836.4 2018.91   875.7 2022.21   937.8 2023.16   973.4  2024.9
#Mann= 6, -1 ,  0
       0     0.1       0     280    0.05       0   430.5   0.045       0
   449.1    0.05       0     560    0.06       0     890    0.05       0
#XS Ineff= 2 , 0
          382.02 1987.66
Permanent Ineff=
       F       F
Bank Sta=430.5,449.1
XS Rating Curve= 0 ,0
Exp/Cntr(USF)=0,0
Exp/Cntr=0.3,0.1

Type RM Length L Ch R = 1 ,6538    ,429,425.3,424.9
XS GIS Cut Line= 2
2308624.53639283737583.675851714 2307890.5165025738278.566005241
#Sta/Elev= 30
       0  2062.2    35.3 2056.61    74.9 2046.82   137.1 2030.05   215.3 2007.47
   267.3 1996.61   287.1 1994.21     328 1987.84   349.3 1981.62   363.5 1980.76
   424.6 1980.73   632.3 1978.49   640.8    1977   652.1 1978.38   669.1 1982.53
     700 1982.94     737 1984.64   749.6 1987.81   760.6 1987.79   768.1  1986.5
   777.1 1988.58   821.2 1994.46   832.2  1995.7     840 1995.38   850.2 1994.12
   886.9 1993.44   942.4 1993.74   957.7 1996.81   988.8 1999.95  1010.8 2003.66
#Mann= 8, -1 ,  0
       0    0.05       0      20     0.1       0     190    0.05       0
   632.3   0.045       0   652.1    0.05       0     700    0.06       0
     760    0.07       0     840    0.05       0
Bank Sta=632.3,652.1
XS Rating Curve= 0 ,0
Exp/Cntr(USF)=0,0
Exp/Cntr=0.3,0.1

Type RM Length L Ch R = 1 ,6113    ,446.9,458.1,449.4
XS GIS Cut Line= 3
2308565.16713699737456.8415324292308280.46456924 737468.98524385
2307735.34685657738062.677802203
#Sta/Elev= 30
       0 2042.53      41 2039.81     105 2033.49   133.1 2029.68   163.8 2024.87
   176.3 2021.64   241.2 2008.08   277.2 2001.36   324.9 1995.34   350.4 1993.25
   426.9 1984.83   456.9  1980.9   474.6 1979.46   486.1 1974.79   504.2 1973.75
   510.1 1974.74   600.2 1975.92   643.6 1975.03   681.6 1975.25   692.5 1976.72
   735.4 1984.53   749.6 1986.22   764.4 1988.86   782.2 1990.84   817.7 1992.88
   839.1  1994.9   877.1 1995.01     911 1998.27     930 1999.44    1091 2006.84
#Mann= 11, -1 ,  0
       0    0.05       0      60     0.1       0     250    0.05       0
   486.1   0.045       0   510.1    0.05       0  614.96    0.06       0
  674.96    0.05       0  754.96    0.06       0  814.96    0.07       0
  884.96    0.06       0  964.96    0.05       0
Bank Sta=486.1,510.1
XS Rating Curve= 0 ,0
Exp/Cntr(USF)=0,0
Exp/Cntr=0.3,0.1

Type RM Length L Ch R = 1 ,5655    ,232.1,225.8,217.8
BEGIN DESCRIPTION:
Structure XS 4
END DESCRIPTION:
XS GIS Cut Line= 2
2308291.25897939737048.0032479262307557.23908906737887.268637235
#Sta/Elev= 30
       0 1986.97    22.9 1984.38    35.1 1985.44      60 1983.13      76 1984.46
    97.2 1982.41     108 1983.97   136.3 1981.79     145 1983.18   170.3 1980.68
   178.8 1981.99   235.6  1978.8   277.9 1978.06   288.5 1979.82   344.9 1979.24
   453.7 1981.74   501.1 1980.93   533.1 1974.41     655 1971.27   660.7 1970.13
   666.4 1971.27     673 1973.26   740.1 1975.35   764.2 1978.54   788.2 1984.49
   812.8 1985.44   824.9 1990.59   833.6 1991.83  1046.2 1996.87    1115 2000.73
#Mann= 13, -1 ,  0
       0     0.1       0     100    0.05       0     120     0.1       0
     230    0.05       0     360    0.06       0     490    0.05       0
     655   0.045       0   666.4    0.05       0     720    0.06       0
     750    0.07       0     860    0.05       0     880    0.07       0
    1010    0.05       0
Bank Sta=655,666.4
XS Rating Curve= 0 ,0
Exp/Cntr(USF)=0,0
Exp/Cntr=0.3,0.1

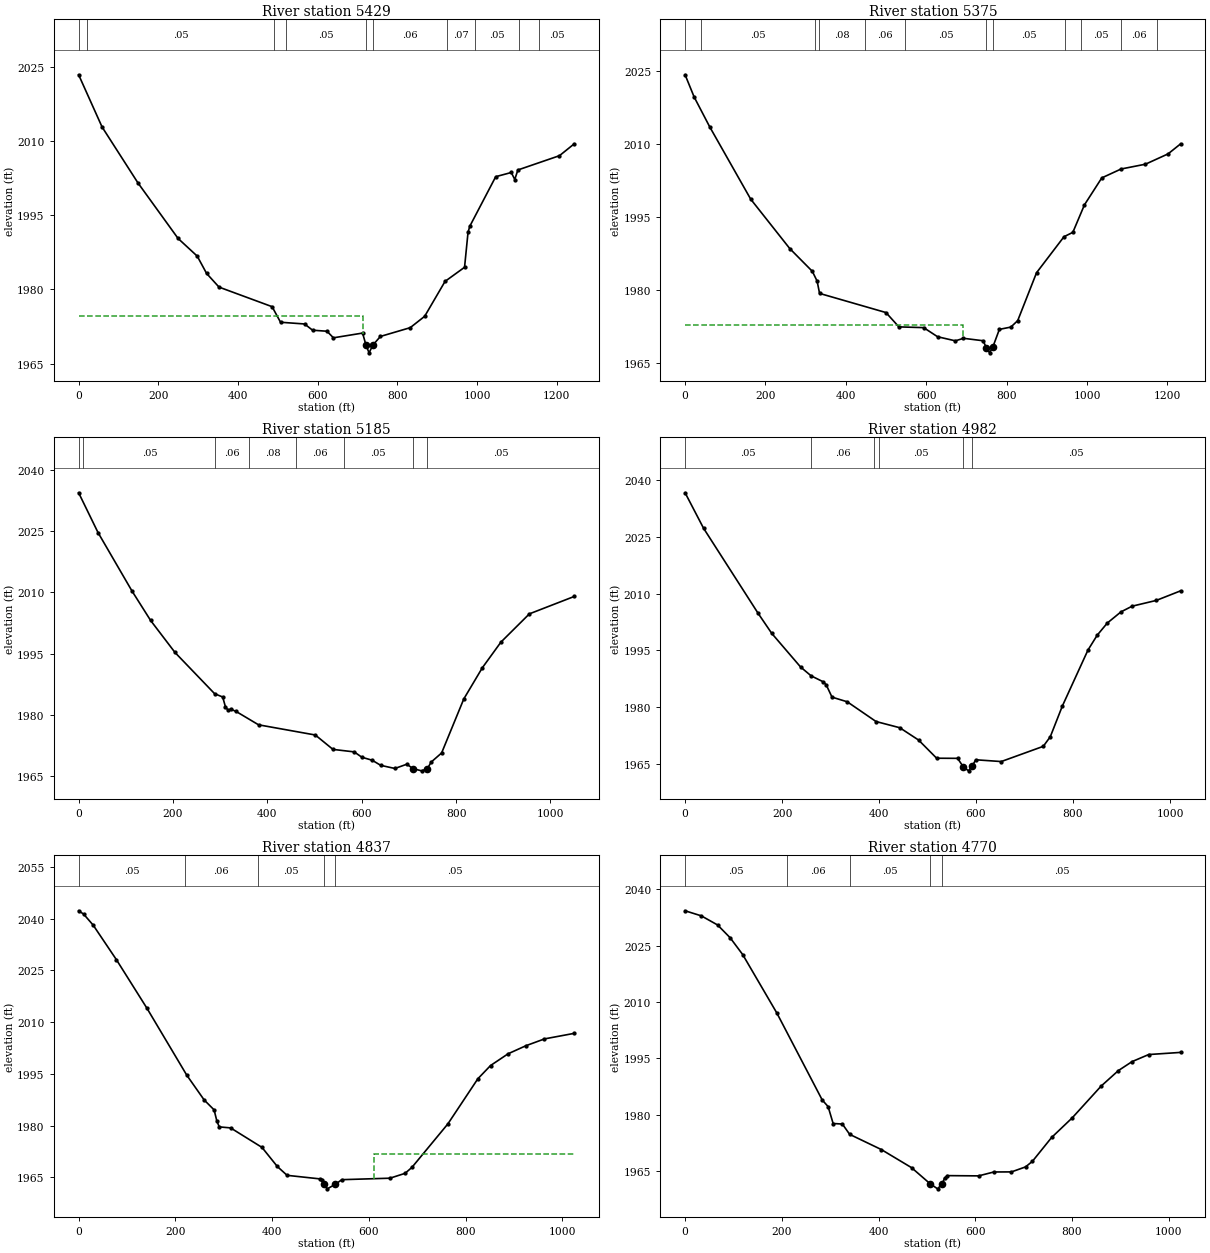
Type RM Length L Ch R = 1 ,5429    ,53.3,53.9,53.9
BEGIN DESCRIPTION:
Structure XS 3
END DESCRIPTION:
XS GIS Cut Line= 6
2307998.14591759736813.9348942692307738.73986191737050.195990011
2307709.18208772737342.8802005912307733.73393612737469.992532171
2307778.95455006737624.0178956482307494.79170281737744.240638716
#Sta/Elev= 30
       0 2023.43    58.8 2012.87   148.8 2001.56   249.6 1990.31   297.6 1986.74
   321.1 1983.24   352.3 1980.47   485.5 1976.51   506.7 1973.36     567 1973.01
   587.1 1971.75   623.3 1971.54   639.4 1970.21   712.6 1971.17   721.3 1968.68
   728.9 1967.17  738.541968.755   757.4 1970.49   832.1 1972.26   868.4 1974.56
   919.6 1981.63   968.5 1984.48   977.2 1991.53   981.5 1992.76  1046.7 2002.81
  1085.8 2003.66  1094.5 2002.24  1102.3 2004.17  1206.7 2007.06  1243.6 2009.45
#Mann= 10, -1 ,  0
       0     0.1       0      20    0.05       0  490.91    0.06       0
  520.91    0.05       0   721.3   0.045       0  738.54    0.06       0
  924.55    0.07       0  995.08    0.05       0 1105.08    0.06       0
 1155.08    0.05       0
#XS Ineff= 2 , 0
          713.08 1974.57
Permanent Ineff=
       F       F
Bank Sta=721.3,738.54
XS Rating Curve= 0 ,0
Exp/Cntr(USF)=0,0
Exp/Cntr=0.3,0.1

Type RM Length L Ch R = 1 ,5375    ,183.9,190,201.9
BEGIN DESCRIPTION:
Structure XS 2
END DESCRIPTION:
XS GIS Cut Line= 6
2307959.67107924736798.2926170552307684.10601651737054.752471619
2307658.58799408737350.1298500432307680.44667464737481.281933388
2307735.09337603737629.9209611792307487.28829467737732.638113266
#Sta/Elev= 30
       0 2024.26    22.5 2019.69    61.2 2013.55   163.2 1998.67   260.4  1988.5
   316.5 1983.82   328.5  1981.8   334.6 1979.27   499.8 1975.33     532 1972.38
   593.5 1972.23   628.3 1970.35   672.5 1969.51   692.7 1970.03   741.4 1969.53
   749.5 1968.13   757.6 1967.04   765.7 1968.24     782 1971.87   810.5 1972.34
   827.6 1973.67   874.5 1983.53   942.7 1990.93   964.8 1991.84   993.7  1997.5
  1036.8 2003.04  1084.8 2004.87  1145.5 2005.86  1201.7 2007.98    1233 2010.05
#Mann= 12, -1 ,  0
       0     0.1       0      40    0.05       0  322.55    0.06       0
  332.55    0.08       0  446.96    0.06       0  546.96    0.05       0
   749.5   0.045       0   765.7    0.05       0   946.4    0.07       0
  984.76    0.05       0 1084.76    0.06       0 1174.76    0.05       0
#XS Ineff= 2 , 0
             692 1972.83
Permanent Ineff=
       F       F
Bank Sta=749.5,765.7
XS Rating Curve= 0 ,0
Exp/Cntr(USF)=0,0
Exp/Cntr=0.3,0.1

Type RM Length L Ch R = 1 ,5185    ,200.8,203.1,209.5
BEGIN DESCRIPTION:
Structure XS 1
END DESCRIPTION:
XS GIS Cut Line= 5
2307926.78544841736763.9187459572307686.80904683737006.708381164
2307623.19450132737236.6029514092307466.84114598 737379.02498173
2307361.55269121737615.462213498
#Sta/Elev= 30
       0 2034.45    41.1 2024.69     113 2010.37   152.6 2003.12   204.2 1995.28
   288.2 1985.16   305.3 1984.35     311    1982   316.7  1981.1   322.4 1981.37
   333.7 1980.81   381.3 1977.53   501.6 1975.03     539  1971.5     584 1970.89
   600.2 1969.58   622.1 1968.84   640.2 1967.59   670.2 1966.82   695.7 1967.87
   708.4 1966.78   726.9 1966.24  739.071966.775   747.1 1968.38   769.3 1970.63
   816.3 1983.88   855.6 1991.53     895 1997.82   955.3 2004.75  1050.2 2009.01
#Mann= 8, -1 ,  0
       0     0.1       0      10    0.05       0     290    0.06       0
  361.37    0.08       0  461.37    0.06       0  561.37    0.05       0
   708.4   0.045       0  739.07    0.05       0
Bank Sta=708.4,739.07
XS Rating Curve= 0 ,0
Exp/Cntr(USF)=0,0
Exp/Cntr=0.3,0.1

Type RM Length L Ch R = 1 ,4982    ,145.9,144.5,142.7
BEGIN DESCRIPTION:
Structure XS 4
END DESCRIPTION:
XS GIS Cut Line= 5
2307914.83653351736759.271797796 2307658.4692924736996.748821137
2307557.47418672737096.5379047432307348.75367888737236.582632585
2307118.85476136737394.993779197
#Sta/Elev= 30
       0 2036.71    38.1 2027.31   150.8 2004.74   178.7 1999.47   238.2 1990.56
   259.9 1988.22   285.3 1986.62   291.2 1985.79     303 1982.58   334.4 1981.35
   393.8 1976.12   442.7 1974.48   481.5 1971.22   518.8  1966.4     562 1966.37
   573.5 1964.17   584.5 1963.06  591.691964.266   599.5 1965.99     652 1965.52
   738.7 1969.55   753.2  1972.1   778.1 1980.24   830.9 1995.06     850    1999
   870.7  2002.2   898.9 2005.16   921.9 2006.67   971.8  2008.2    1022 2010.74
#Mann= 6, -1 ,  0
       0    0.05       0     260    0.06       0  389.46    0.08       0
  399.46    0.05       0   573.5   0.045       0  591.69    0.05       0
Bank Sta=573.5,591.69
XS Rating Curve= 0 ,0
Exp/Cntr(USF)=0,0
Exp/Cntr=0.3,0.1

Type RM Length L Ch R = 1 ,4837    ,67.7,67.2,67.5
BEGIN DESCRIPTION:
Structure XS 3
END DESCRIPTION:
XS GIS Cut Line= 2
2307820.14154028736686.7938655962307031.04317215737340.368414266
#Sta/Elev= 30
       0 2042.33    10.3 2041.37    30.1 2038.16    77.9 2028.18   140.9 2014.12
   223.6 1994.61   259.6 1987.41   280.1 1984.54   285.9 1981.25   290.8  1979.6
   314.2 1979.31   379.1 1973.65   410.8 1968.11     431 1965.54   498.8 1964.51
   503.8 1964.32   507.3 1962.96   514.1 1961.62   530.5 1962.92   544.3 1964.28
   643.7 1964.71     675 1966.12   689.2 1967.86   763.5 1980.48   825.5 1993.58
   851.7 1997.41   888.1 2000.83     925 2003.17   963.2 2005.14  1024.6 2006.75
#Mann= 5, -1 ,  0
       0    0.05       0     220    0.06       0     370    0.05       0
   507.3   0.045       0   530.5    0.05       0
#XS Ineff= 2 , 0
                          611.71         1971.75
Permanent Ineff=
       F       F
Bank Sta=507.3,530.5
XS Rating Curve= 0 ,0
Exp/Cntr(USF)=0,0
Exp/Cntr=0.3,0.1

Type RM Length L Ch R = 1 ,4770    ,171.2,173.4,173.8
BEGIN DESCRIPTION:
Structure XS 2
END DESCRIPTION:
XS GIS Cut Line= 2
2307783.90270478736629.7118097512306994.80433665737283.286358421
#Sta/Elev= 30
       0 2034.28    33.5 2032.93    67.2  2030.5    93.2 2027.09   119.1 2022.62
   189.8 2007.04   283.5 1983.92   295.7 1982.15   306.1 1977.65   325.2 1977.51
   340.3 1974.76   405.7 1970.72   468.2  1965.9   507.1 1961.56   522.2 1960.26
  531.561961.647   536.4 1963.05     542 1963.78   606.8 1963.71   638.5 1964.75
   674.8 1964.77     704  1966.1   718.2  1967.6   757.9 1973.94   800.6 1979.18
   860.2 1987.61   895.9 1991.74   924.2 1994.13   958.6 1996.01  1024.6 1996.58
#Mann= 5, -1 ,  0
       0    0.05       0     210    0.06       0     340    0.05       0
   507.1   0.045       0  531.56    0.05       0
Bank Sta=507.1,531.56
XS Rating Curve= 0 ,0
Exp/Cntr(USF)=0,0
Exp/Cntr=0.3,0.1