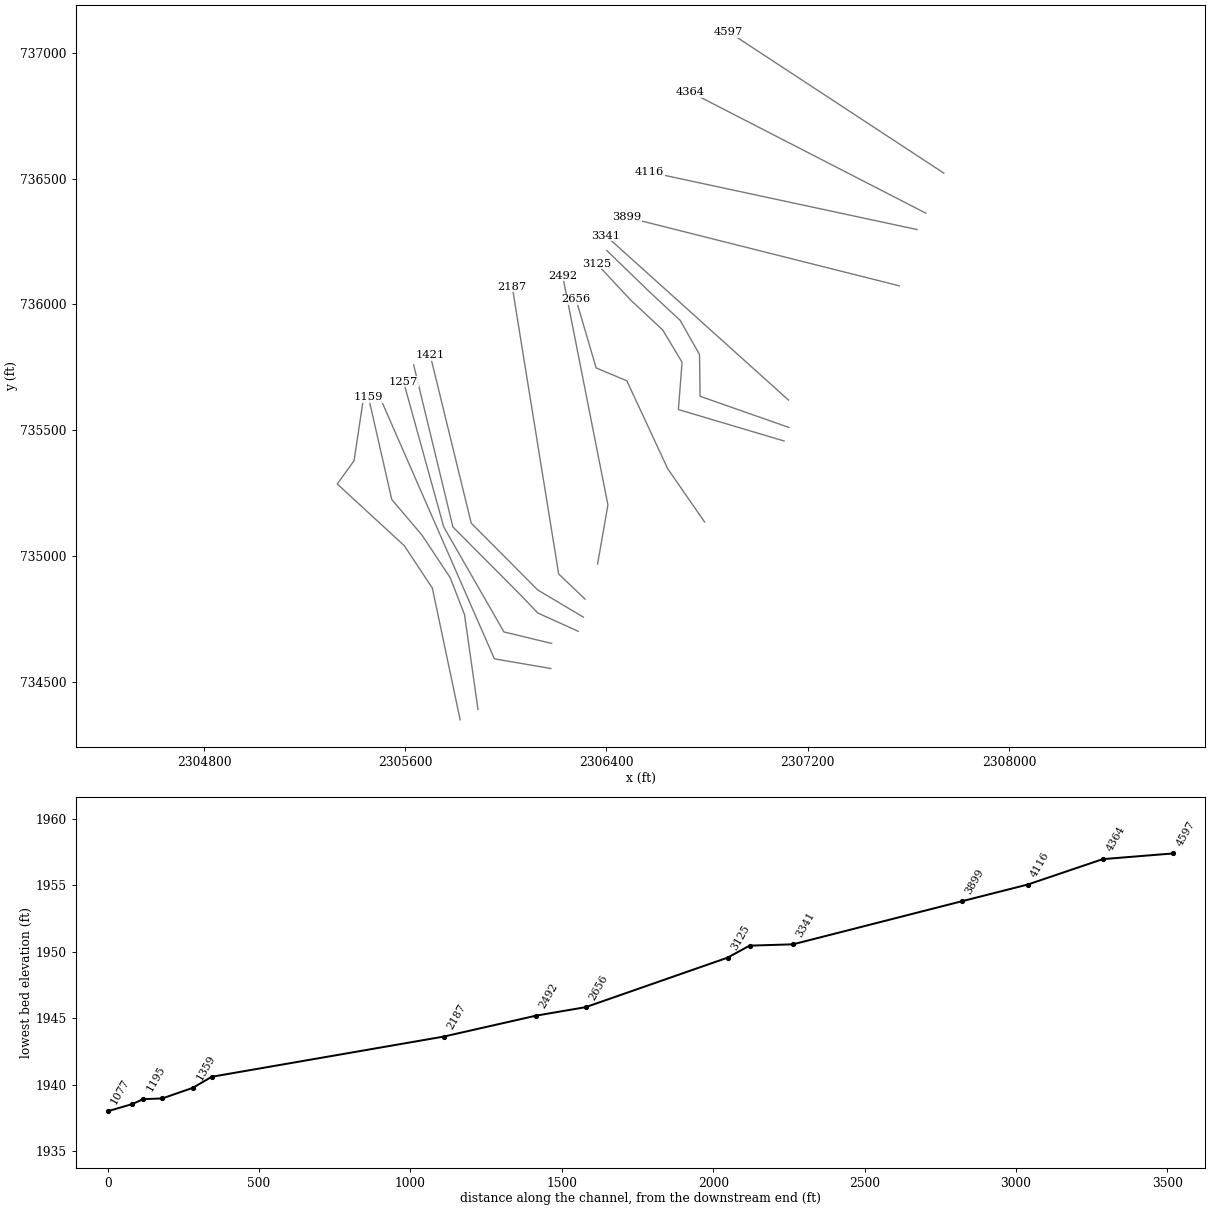
HEC-RAS study LAZYRN.prj: LAZYRN

--- LAZYRN.g01 (geometry) --- (continued)

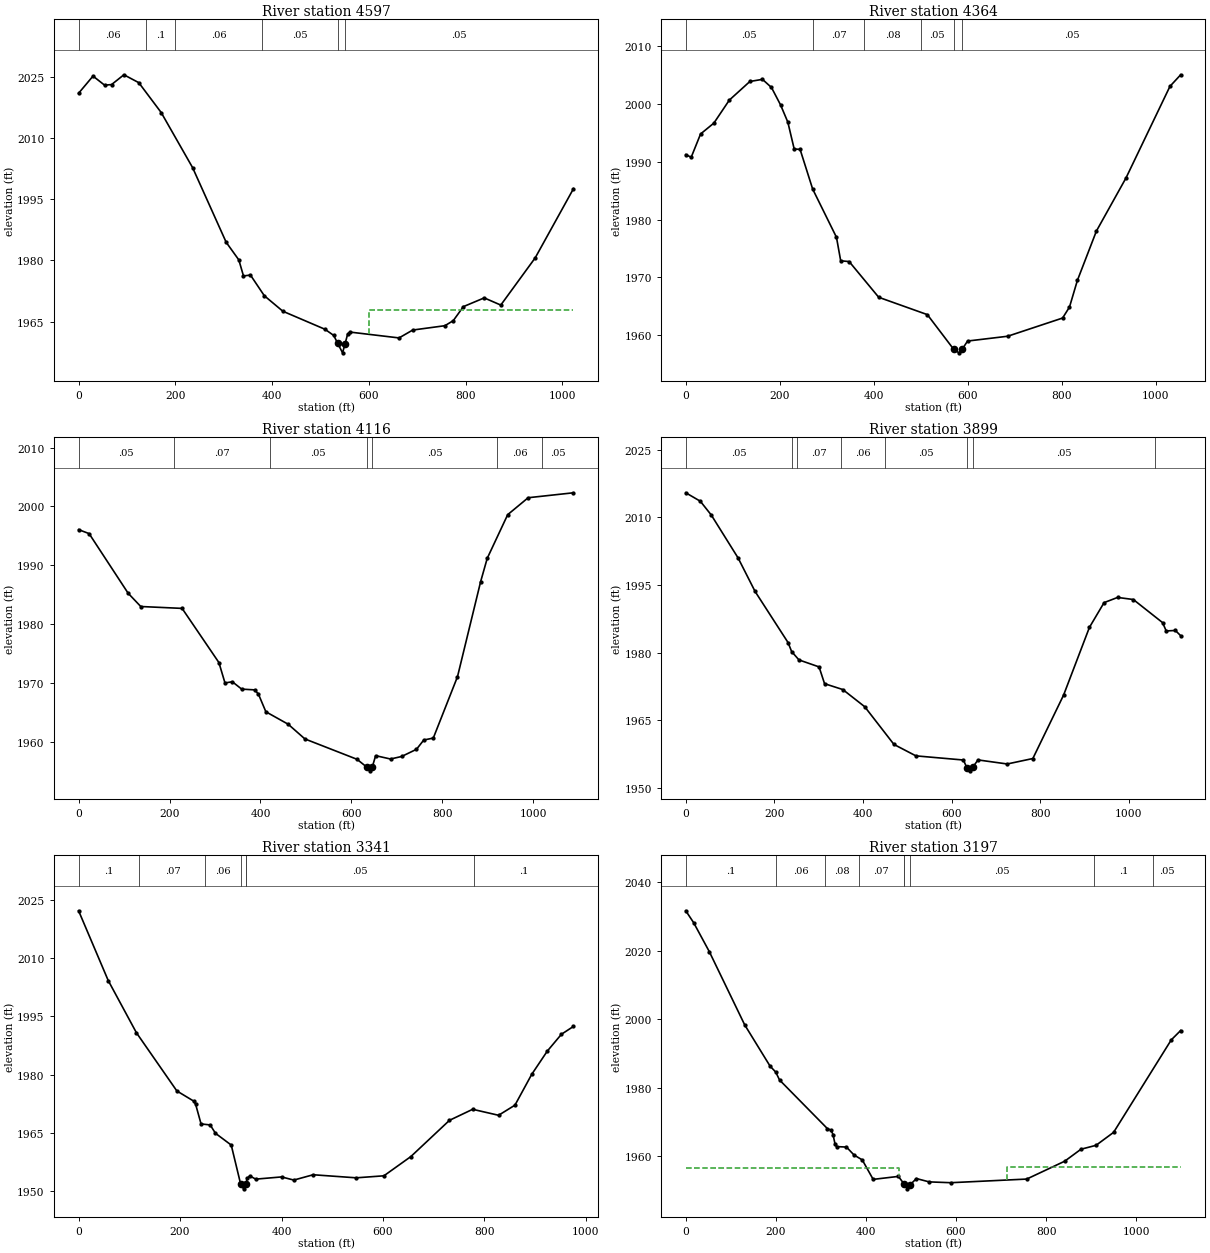
Type RM Length L Ch R = 1 ,4597    ,232.8,233.4,234.8
BEGIN DESCRIPTION:
Structure XS 1
END DESCRIPTION:
XS GIS Cut Line= 2
2307741.10537454 736521.801749562306885.92821508737083.067090236
#Sta/Elev= 30
       0 2020.93    29.8 2025.13    53.7 2022.91    68.1 2023.05    93.6 2025.45
   124.4 2023.52   170.7 2016.21   235.6 2002.73     305 1984.46   331.2 1980.13
   340.8 1976.21   355.2 1976.43   383.9 1971.36   422.2 1967.57   509.2 1963.16
   527.4 1961.64  535.631959.677   545.6 1957.39  550.821959.633   556.1 1961.99
   560.9 1962.47   662.3 1961.04   690.6 1962.97   757.1 1964.03   774.4 1965.27
   795.3  1968.7   838.4 1970.84   872.6 1969.08   943.7 1980.63  1022.9 1997.58
#Mann= 6, -1 ,  0
       0    0.06       0     140     0.1       0     200    0.06       0
     380    0.05       0  535.63   0.045       0  550.82    0.05       0
#XS Ineff= 2 , 0
                          600.68          1967.9
Permanent Ineff=
       F       F
Bank Sta=535.63,550.82
XS Rating Curve= 0 ,0
Exp/Cntr(USF)=0,0
Exp/Cntr=0.3,0.1

Type RM Length L Ch R = 1 ,4364    ,246.7,247.9,248.3
XS GIS Cut Line= 2
2307669.35520012736362.7876744512306732.73259691736844.378124495
#Sta/Elev= 30
       0 1991.24    11.6  1990.8    31.5 1994.82    59.8  1996.7    92.7 2000.68
   136.4  2003.9   163.2 2004.27   182.4 2002.86   201.7 1999.85   217.2 1996.87
   230.7 1992.23   243.3 1992.15     270  1985.3   320.7 1976.95   329.7 1972.88
   347.7 1972.75   410.6 1966.57   514.1 1963.57     570 1957.59   581.5 1956.96
  588.231957.584   599.7    1959     685 1959.83   801.9 1962.98   816.6 1964.88
   833.4 1969.49   873.9 1978.03   936.9 1987.22  1030.4 2003.06  1053.2 2005.06
#Mann= 6, -1 ,  0
       0    0.05       0     270    0.07       0     380    0.08       0
     500    0.05       0     570   0.045       0  588.23    0.05       0
Bank Sta=570,588.23
XS Rating Curve= 0 ,0
Exp/Cntr(USF)=0,0
Exp/Cntr=0.3,0.1

Type RM Length L Ch R = 1 ,4116    ,216.6,216.7,216.1
XS GIS Cut Line= 2
2307634.79311797736297.4547768672306570.69068975736525.856130013
#Sta/Elev= 30
       0 1996.05    23.1 1995.37     109 1985.23   136.7 1982.98   227.6 1982.66
   308.5 1973.46   321.9 1969.99   338.1 1970.19   358.6 1968.94   387.2 1968.81
   395.4  1968.1   411.8 1965.09   460.9 1962.97   497.7 1960.47   612.3 1957.01
   634.1 1955.66   640.9 1955.05  645.821955.699   653.2 1957.63   685.9 1957.06
   710.4 1957.49     743 1958.71   759.1 1960.29     780 1960.62   833.2 1971.05
   884.1 1987.21   898.6 1991.17   943.6 1998.59   988.6 2001.47  1088.3 2002.31
#Mann= 7, -1 ,  0
       0    0.05       0     210    0.07       0     420    0.05       0
   634.1   0.045       0  645.82    0.05       0     920    0.06       0
    1020    0.05       0
Bank Sta=634.1,645.82
XS Rating Curve= 0 ,0
Exp/Cntr(USF)=0,0
Exp/Cntr=0.3,0.1

Type RM Length L Ch R = 1 ,3899    ,553.1,558.3,551.6
XS GIS Cut Line= 2
 2307563.9855954736073.8077317192306480.49667641736346.366588054
#Sta/Elev= 30
       0 2015.44    32.8 2013.57    57.5 2010.52     118 2001.01   156.5 1993.56
   230.8 1982.25     239 1980.24   255.5 1978.39   300.9 1976.84   313.3 1973.12
   354.5 1971.82     404 1968.01     470 1959.65   519.5 1957.12   626.7  1956.2
   634.4 1954.52     642  1953.8   647.4 1954.55   659.7 1956.22   725.7 1955.32
   783.5 1956.53   852.9 1970.59   911.3 1985.62   944.3 1991.09   974.8 1992.24
  1010.3 1991.78  1076.3 1986.66  1084.6 1984.81  1105.2 1984.92  1117.2 1983.76
#Mann= 8, -1 ,  0
       0    0.05       0     240    0.06       0     250    0.07       0
     350    0.06       0     450    0.05       0   634.4   0.045       0
   647.4    0.05       0    1060     0.1       0
Bank Sta=634.4,647.4
XS Rating Curve= 0 ,0
Exp/Cntr(USF)=0,0
Exp/Cntr=0.3,0.1

Type RM Length L Ch R = 1 ,3341    ,147.1,143.5,137.1
BEGIN DESCRIPTION:
Structure XS 4
END DESCRIPTION:
XS GIS Cut Line= 3
2307123.61573824735619.6369318152306419.62819694736253.114878131
2306398.71026422736272.507590682
#Sta/Elev= 30
       0 2022.23    58.4 2004.25     114 1990.79   193.7 1975.79   227.3 1973.14
   230.6 1972.41   241.4 1967.29   259.4 1967.03   269.8 1964.88   300.9 1961.84
   319.2 1951.92   325.2 1950.56   329.6  1951.9   332.9 1953.35   337.7 1953.89
   349.1 1953.06   400.1 1953.63   424.3 1952.82   462.4 1954.19   547.3  1953.4
   601.9 1953.92     655 1958.88   731.1 1968.22   776.8 1971.06   827.9 1969.52
   860.2 1972.13   893.3 1980.08     924 1986.07   951.8  1990.4   975.6 1992.43
#Mann= 7, -1 ,  0
       0     0.1       0     120    0.07       0     250    0.06       0
   319.2   0.045       0   329.6    0.06       0     330    0.05       0
     780     0.1       0
Bank Sta=319.2,329.6
XS Rating Curve= 0 ,0
Exp/Cntr(USF)=0,0
Exp/Cntr=0.3,0.1

Type RM Length L Ch R = 1 ,3197    ,73.3,72.3,71.5
BEGIN DESCRIPTION:
Structure XS 3
END DESCRIPTION:
XS GIS Cut Line= 6
2307124.64880597735511.0606583782306772.17677544735634.679825295
2306770.03492841735800.3833485662306693.31095966735936.125754828
2306567.89677996736052.8838970262306401.21155201736214.326610343
#Sta/Elev= 30
       0 2031.61    17.5 2028.13    52.2  2019.7   130.7 1998.34     187  1986.3
   199.7 1984.53   208.2 1982.22   314.2 1968.06   322.7 1967.55   326.9  1966.3
   331.5 1963.43   334.7 1962.79   356.7 1962.65   373.5 1960.34   391.8  1958.9
     416 1953.22     472 1954.09  485.441951.731     492 1950.46  498.241951.686
     512 1953.46   540.2 1952.49   588.2 1952.25   756.8 1953.31   841.1 1958.52
   877.3 1962.02   910.7 1963.16   949.7 1966.94  1077.7 1993.93  1098.6 1996.67
#Mann= 9, -1 ,  0
       0     0.1       0     200    0.06       0     310    0.08       0
  383.52    0.07       0  483.52    0.05       0  485.44   0.045       0
  498.24    0.05       0  906.51     0.1       0 1036.51    0.05       0
#XS Ineff= 2 , 0
          472.23 1956.43  712.99         1956.72
Permanent Ineff=
       F       F
Bank Sta=485.44,498.24
XS Rating Curve= 0 ,0
Exp/Cntr(USF)=0,0
Exp/Cntr=0.3,0.1

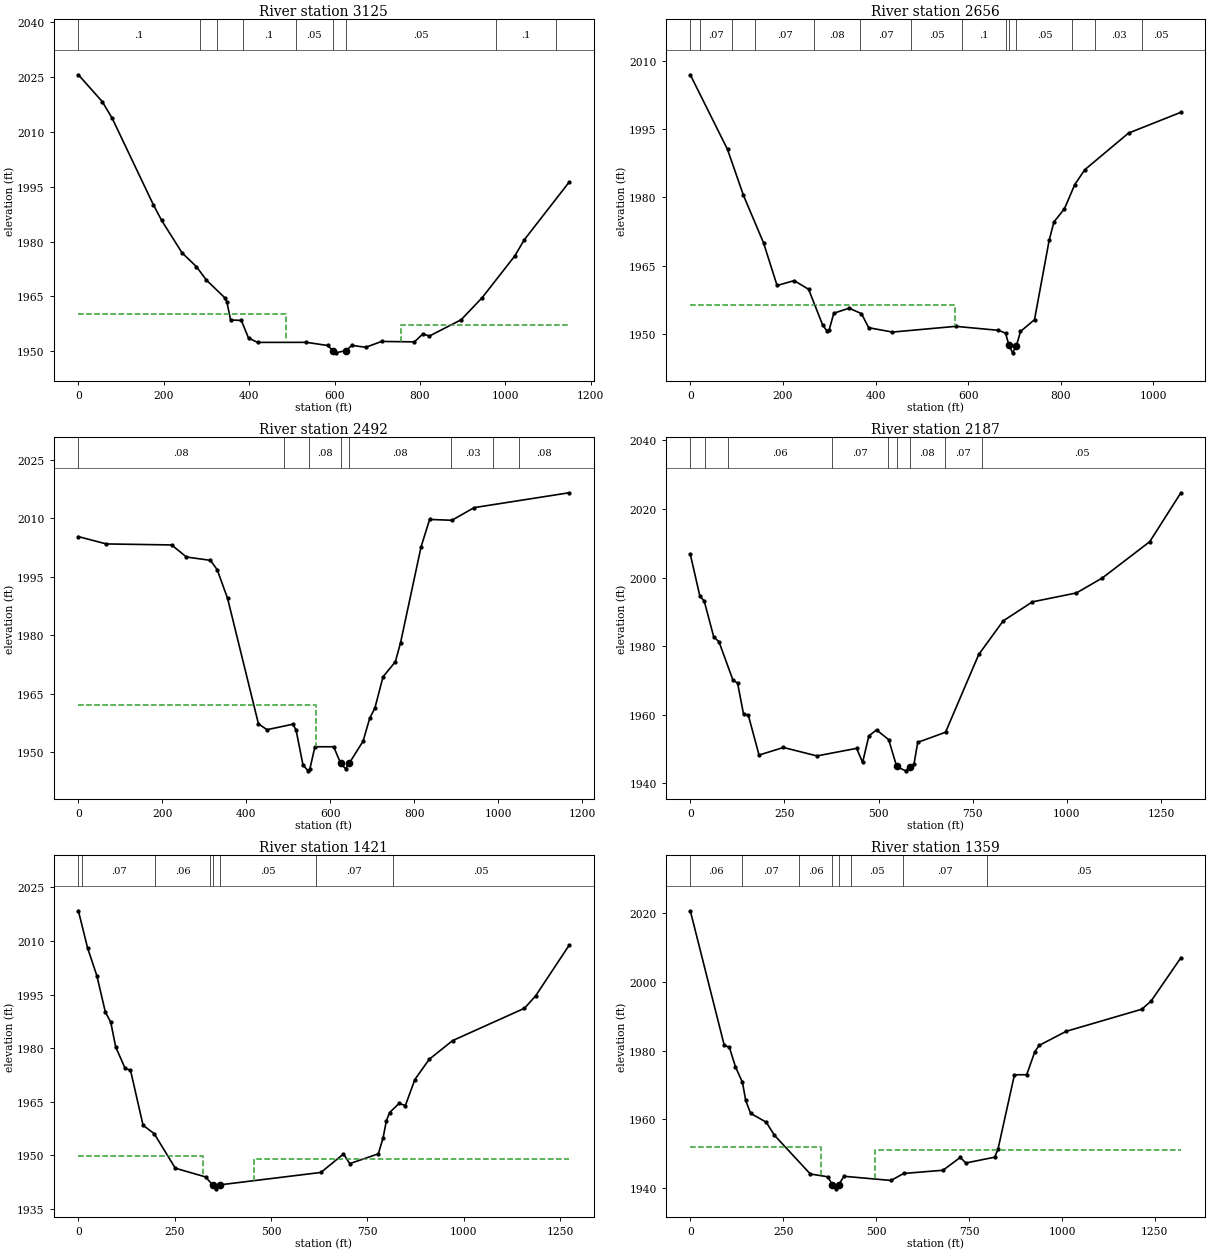
Type RM Length L Ch R = 1 ,3125    ,446.7,468.8,466.6
BEGIN DESCRIPTION:
Structure XS 2
END DESCRIPTION:
XS GIS Cut Line= 6
 2307106.3209312735456.9545872432306685.95197817735581.927985349
2306700.62027028735769.8635099572306623.44715704735898.644176552
2306498.03297734 736015.402318752306361.27183652736161.882988494
#Sta/Elev= 30
       0 2025.67      56 2018.31    79.3 2013.74   175.4 1990.15   195.1 1985.79
   242.9 1976.92   276.6 1973.14   299.8 1969.48   343.9 1964.53   348.1 1963.37
   356.5 1958.56   381.7 1958.43   398.5 1953.61   419.6 1952.42   534.3 1952.43
   583.5 1951.58   596.61950.144   602.5 1949.56   627.2 1950.19   640.4 1951.59
   673.1 1951.09   710.4 1952.68     787 1952.56   806.9 1954.74   822.2 1954.15
   896.6 1958.62   945.8 1964.67  1022.3  1976.1  1044.2 1980.47  1149.1 1996.23
#Mann= 9, -1 ,  0
       0     0.1       0  284.53    0.07       0  324.53    0.08       0
  384.53     0.1       0  508.72    0.05       0   596.6   0.045       0
   627.2    0.05       0  978.71     0.1       0 1118.71    0.05       0
#XS Ineff= 2 , 0
          486.09 1960.24   754.6         1957.14
Permanent Ineff=
       F       F
Bank Sta=596.6,627.2
XS Rating Curve= 0 ,0
Exp/Cntr(USF)=0,0
Exp/Cntr=0.3,0.1

Type RM Length L Ch R = 1 ,2656    ,172.8,164.2,155
XS GIS Cut Line= 5
2306790.01403826735135.1006075482306643.64489018735346.522710334
2306481.01250342735696.1823418642306359.03821335735747.295377702
2306278.88367988736020.285455475
#Sta/Elev= 30
       0 2006.91    80.4 1990.51   114.9  1980.4   158.1 1970.02   187.4 1960.63
   224.2  1961.7   255.5  1959.8   285.8 1951.97   294.9 1950.68   299.8 1950.83
   309.9 1954.54   343.1 1955.65   369.7 1954.45   385.2 1951.36   436.5  1950.4
   573.3 1951.66   665.6 1950.78   680.9 1950.16   688.31947.452   696.1 1945.84
   704.4 1947.44   713.1 1950.53   743.4 1953.13     775 1970.55   785.3 1974.59
   807.9 1977.46   830.4 1982.81     852 1986.06   946.4  1994.1  1059.5 1998.67
#Mann= 14, -1 ,  0
       0    0.08       0      20    0.07       0      90    0.08       0
     140    0.07       0  267.14    0.08       0  367.14    0.07       0
  477.14    0.05       0  587.14     0.1       0  682.78    0.05       0
   688.3   0.045       0   704.4    0.05       0  825.03    0.08       0
  875.03    0.03       0  975.03    0.05       0
#XS Ineff= 2 , 0
             571 1956.45
Permanent Ineff=
       F       F
Bank Sta=688.3,704.4
XS Rating Curve= 0 ,0
Exp/Cntr(USF)=0,0
Exp/Cntr=0.3,0.1

Type RM Length L Ch R = 1 ,2492    ,318,304.3,305.9
BEGIN DESCRIPTION:
Structure XS 3
END DESCRIPTION:
XS GIS Cut Line= 3
 2306364.7439676 734967.692960762306405.79209812735202.579485374
2306225.63641419736114.760163486
#Sta/Elev= 30
       0 2005.32    66.5 2003.44     222 2003.18   257.4 2000.08   314.5 1999.23
   330.6 1996.81   355.3 1989.45   428.7 1957.28     449 1955.76     511 1957.17
   518.4 1955.65   534.8 1946.73   546.9  1945.2     551 1945.59   563.2 1951.38
     608 1951.38   624.4 1947.14   636.6 1945.68  644.87 1947.15   677.9  1952.8
   693.7 1958.69   705.9 1961.27   725.5 1969.35   754.8  1973.2   767.1 1978.07
     816 2002.69   836.4 2009.73   889.4 2009.51   942.4 2012.76  1168.2 2016.57
#Mann= 8, -1 ,  0
       0    0.08       0  488.45    0.07       0  548.45    0.08       0
   624.4   0.045       0  644.87    0.08       0  888.45    0.03       0
  988.45    0.05       0 1048.45    0.08       0
#XS Ineff= 2 , 0
          565.06 1962.16
Permanent Ineff=
       F       F
Bank Sta=624.4,644.87
XS Rating Curve= 0 ,0
Exp/Cntr(USF)=0,0
Exp/Cntr=0.3,0.1

Type RM Length L Ch R = 1 ,2187    ,724.1,766.4,764.6
BEGIN DESCRIPTION:
Structure XS 2
END DESCRIPTION:
XS GIS Cut Line= 3
2306314.91275444734828.1096372922306210.01197646734928.449511884
2306025.29538914 736070.95581122
#Sta/Elev= 30
       0 2006.78    25.3 1994.64      37 1993.12    62.1 1982.75    76.3 1981.23
     113 1970.16   125.6 1969.18   141.3 1960.18     154 1959.88   182.5 1948.23
   247.2 1950.44   336.3 1947.98   441.7 1950.19   457.4 1946.07   474.1 1953.81
   494.4 1955.57   526.8 1952.71   547.91944.912   571.4 1943.63   583.7 1944.88
   593.9 1945.58   603.8 1951.93   677.6 1954.88   765.8 1977.56   830.7 1987.35
   908.5 1992.91  1025.2  1995.5  1094.1 1999.88  1219.7 2010.44  1302.5 2024.71
#Mann= 9, -1 ,  0
       0    0.07       0      40    0.08       0     100    0.06       0
  375.16    0.07       0  525.16    0.05       0   547.9   0.045       0
   583.7    0.08       0  675.16    0.07       0  775.16    0.05       0
Bank Sta=547.9,583.7
XS Rating Curve= 0 ,0
Exp/Cntr(USF)=0,0
Exp/Cntr=0.3,0.1

Type RM Length L Ch R = 1 ,1421    ,62.5,62.5,62.5
BEGIN DESCRIPTION:
Structure XS 3
END DESCRIPTION:
XS GIS Cut Line= 4
2306308.37454029734756.7221723042306127.00728529734864.561726253
2305862.38889407735130.449224715 2305699.5709633735797.535819058
#Sta/Elev= 30
       0 2018.46    23.8 2008.08    47.9 2000.29      70 1990.09      84 1987.26
    96.8 1980.35   121.2 1974.34   135.2 1973.82   167.8 1958.41   196.6 1956.07
   251.4 1946.39   330.4 1943.93348.0694 1941.68   356.8 1940.61366.56941941.721
   629.2  1945.2   687.8 1950.36   704.2 1947.67   778.3 1950.42   790.7 1954.97
   798.9 1959.58   807.2 1961.94   831.9 1964.51   848.4 1963.94     873 1971.22
   910.1 1976.86   970.8 1982.11  1157.1 1991.15    1186 1994.59  1272.8 2008.74
#Mann= 8, -1 ,  0
       0    0.06       0      10    0.07       0     200    0.06       0
  341.01    0.05       0348.0694   0.045       0366.5694    0.05       0
  616.13    0.07       0  816.13    0.05       0
#XS Ineff= 2 , 0
          322.78 1949.75  455.58         1949.04
Permanent Ineff=
       F       F
Bank Sta=348.0694,366.5694
XS Rating Curve= 0 ,0
Exp/Cntr(USF)=0,0
Exp/Cntr=0.3,0.1

Type RM Length L Ch R = 1 ,1359    ,103.1,101.1,98.7
BEGIN DESCRIPTION:
Structure XS 2
END DESCRIPTION:
XS GIS Cut Line= 5
2306288.07246494734700.3701282592306127.15856482734773.092344769
2306054.25482095734849.2578127242305789.63642973735115.145311186
2305633.65985405735759.427388576
#Sta/Elev= 30
       0 2020.76    91.2 1981.64   105.2 1980.96   121.5 1975.34   140.4 1970.76
   149.1 1965.52   162.3 1961.76   204.2  1959.2   226.5 1955.37     323  1944.1
     370 1943.29382.46981940.949   390.9 1939.78399.36981941.004   413.5 1943.44
   540.1 1942.22   574.2 1944.26   679.9 1945.19   726.3 1948.92   741.5 1947.31
   819.1    1949     828 1951.38   872.1 1972.99   905.2 1973.02   926.7 1979.64
   938.4 1981.54  1011.3 1985.65  1214.8 1992.09  1239.9 1994.47    1320 2007.08
#Mann= 8, -1 ,  0
       0    0.06       0     140    0.07       0  292.02    0.06       0
382.4698   0.045       0399.3698    0.06       0  432.02    0.05       0
  572.02    0.07       0  797.14    0.05       0
#XS Ineff= 2 , 0
          352.18 1952.02   496.7         1951.18
Permanent Ineff=
       F       F
Bank Sta=382.4698,399.3698
XS Rating Curve= 0 ,0
Exp/Cntr(USF)=0,0
Exp/Cntr=0.3,0.1

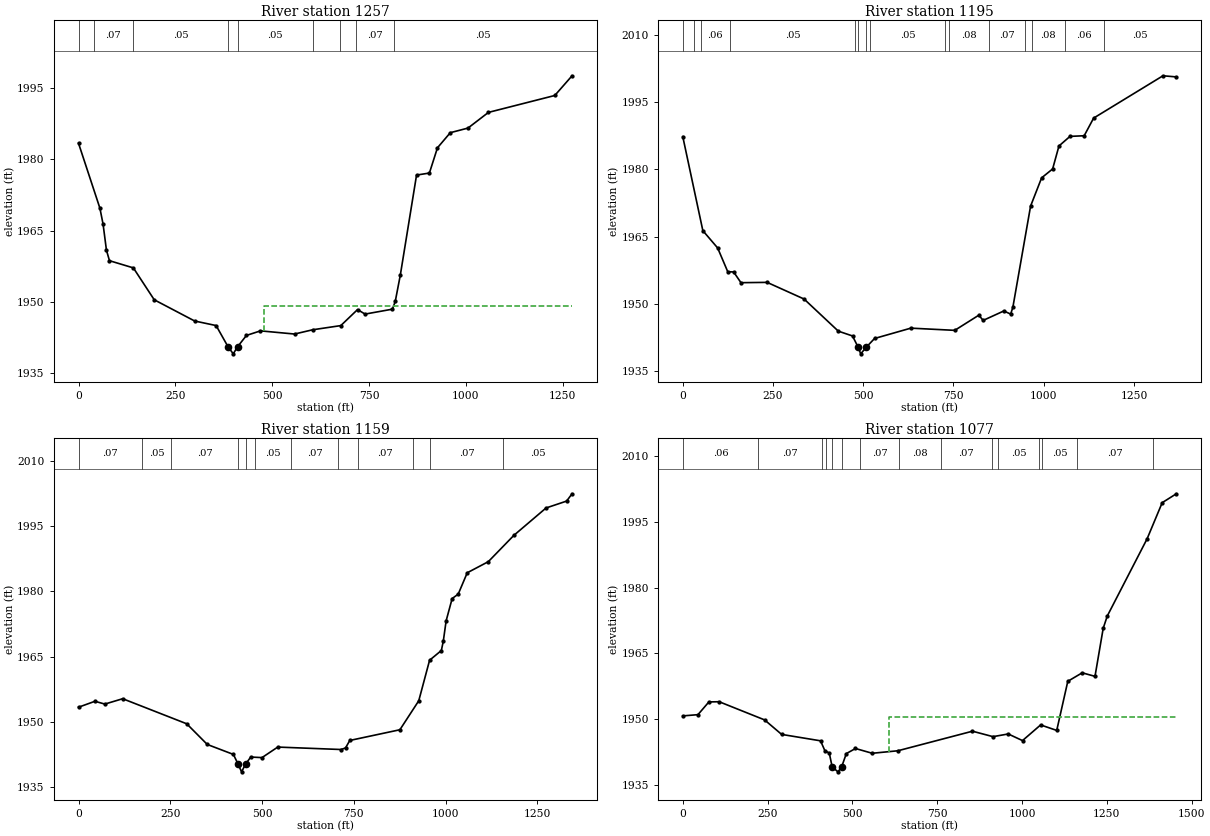
Type RM Length L Ch R = 1 ,1257    ,60.6,62.6,58
BEGIN DESCRIPTION:
Structure XS 1
END DESCRIPTION:
XS GIS Cut Line= 4
2306181.84798402734652.2852311752305992.57049332 734697.89426508
2305753.12306531735115.2169253162305593.49144664735692.171204221
#Sta/Elev= 30
       0 1983.42    55.2 1969.72    63.4 1966.35    72.1 1960.85    79.9 1958.64
   141.6 1957.12   195.5 1950.39   299.9 1945.91   355.3 1944.95386.49981940.416
   399.6 1938.98410.65981940.473   433.7 1942.87   469.9 1943.83   557.8 1943.16
   604.7 1944.06   677.3 1944.94   720.5 1948.32     740 1947.37   810.7 1948.41
     818 1950.08     831  1955.6   872.9 1976.71   906.1 1977.14   926.9 1982.47
   960.1 1985.66  1005.7 1986.63  1058.5 1989.94  1229.9 1993.51  1274.5 1997.67
#Mann= 9, -1 ,  0
       0    0.06       0      40    0.07       0     140    0.05       0
386.4998   0.045       0410.6598    0.05       0   604.7    0.07       0
   674.7    0.08       0  715.83    0.07       0  815.83    0.05       0
#XS Ineff= 2 , 0
                          478.53         1949.08
Permanent Ineff=
       F       F
Bank Sta=386.4998,410.6598
XS Rating Curve= 0 ,0
Exp/Cntr(USF)=0,0
Exp/Cntr=0.3,0.1

Type RM Length L Ch R = 1 ,1195    ,36.4,36,35.2
BEGIN DESCRIPTION:
Structure XS 4
END DESCRIPTION:
XS GIS Cut Line= 3
2306179.01345942734552.4317866452305954.60138659734590.942660982
2305497.52275799735635.037222635
#Sta/Elev= 30
       0 1987.28    55.6 1966.35    96.6  1962.5   124.6 1957.21   140.9 1957.16
   161.2 1954.77   233.7 1954.84   336.1 1951.13     431 1943.98   470.3 1942.91
485.21951940.506   493.1 1938.93  508.821940.445   531.4 1942.35   631.9 1944.65
   753.6 1944.16   820.4 1947.54   832.2 1946.37   889.5 1948.47   908.5 1947.78
   914.6 1949.29   963.7 1971.82   994.3 1978.11  1024.8 1980.09  1042.3  1985.2
  1072.9 1987.34  1112.2 1987.48  1138.4 1991.41  1330.5 2000.83  1367.5 2000.58
#Mann= 15, -1 ,  0
       0    0.06       0      30    0.05       0      50    0.06       0
     130    0.05       0  477.69    0.07       0485.2195   0.045       0
  508.82    0.07       0  517.69    0.05       0  727.69    0.07       0
  737.69    0.08       0  847.69    0.07       0  947.69    0.05       0
  967.69    0.08       0 1057.69    0.06       0 1167.69    0.05       0
Bank Sta=485.2195,508.82
XS Rating Curve= 0 ,0
Exp/Cntr(USF)=0,0
Exp/Cntr=0.3,0.1

Type RM Length L Ch R = 1 ,1159    ,82,81.7,81.6
BEGIN DESCRIPTION:
Structure XS 3
END DESCRIPTION:
XS GIS Cut Line= 6
2305889.34512391734389.8179946882305835.69184141 734767.06303964
2305778.85927196734913.5161993752305667.38000112735081.828039668
2305546.57374169735224.3692308562305453.93402267735631.667922012
#Sta/Elev= 30
       0 1953.41    44.7 1954.77    71.7 1954.13   120.3 1955.36   294.8  1949.6
   350.8 1944.85     422 1942.56   434.9 1940.29   444.2 1938.56   455.21940.339
   469.2 1941.96   499.9 1941.83   542.8 1944.25   715.4 1943.69   727.5 1944.06
   739.1 1945.77   875.6 1948.23     927 1954.89   956.5  1964.2   988.6 1966.44
   993.9  1968.6  1001.6 1973.26    1018 1978.38  1034.5 1979.39  1059.1  1984.3
  1116.5 1986.85  1186.2  1992.9  1273.9 1999.19  1329.8 2000.77  1344.7 2002.45
#Mann= 12, -1 ,  0
       0    0.07       0  172.73    0.05       0  252.73    0.07       0
   434.9   0.045       0   455.2    0.07       0  481.14    0.05       0
  578.24    0.07       0  708.24    0.08       0  760.12    0.07       0
  910.12    0.06       0  956.97    0.07       0 1156.97    0.05       0
Bank Sta=434.9,455.2
XS Rating Curve= 0 ,0
Exp/Cntr(USF)=0,0
Exp/Cntr=0.3,0.1

Type RM Length L Ch R = 1 ,1077    ,155.9,156.7,157.4
BEGIN DESCRIPTION:
Structure XS 2
END DESCRIPTION:
XS GIS Cut Line= 6
2305818.36306509734348.6810679312305707.87721314734872.379272618
 2305596.3979423735040.6911129112305329.93083064735285.941426628
2305396.63467402735378.4489875942305432.13558527735614.321182687
#Sta/Elev= 30
       0 1950.77    44.7 1951.05    76.9 1953.95   107.2    1954   241.1 1949.86
   291.4 1946.55   406.1 1945.09     419 1942.81   431.8 1942.31   440.4 1939.12
   457.6 1938.02  468.281939.159   482.1 1942.18   509.1 1943.34   558.4 1942.25
   633.8 1942.82   853.9 1947.28   914.4 1946.04   959.4 1946.65  1001.4 1945.14
  1054.8 1948.71  1102.3 1947.46  1134.9 1958.65  1177.4 1960.59  1215.1 1959.78
  1239.3 1970.74  1251.4 1973.55  1368.7 1991.13  1413.2 1999.36  1454.8 2001.39
#Mann= 15, -1 ,  0
       0    0.06       0  222.73    0.07       0  411.14    0.05       0
  421.14    0.06       0   440.4   0.045       0  468.28    0.06       0
  521.14    0.07       0  638.24    0.08       0  760.12    0.07       0
  910.12    0.06       0  930.12    0.05       0 1050.12    0.07       0
 1060.12    0.05       0 1162.27    0.07       0 1386.32    0.05       0
#XS Ineff= 2 , 0
                          608.58         1950.49
Permanent Ineff=
       F       F
Bank Sta=440.4,468.28
XS Rating Curve= 0 ,0
Exp/Cntr(USF)=0,0
Exp/Cntr=0.3,0.1