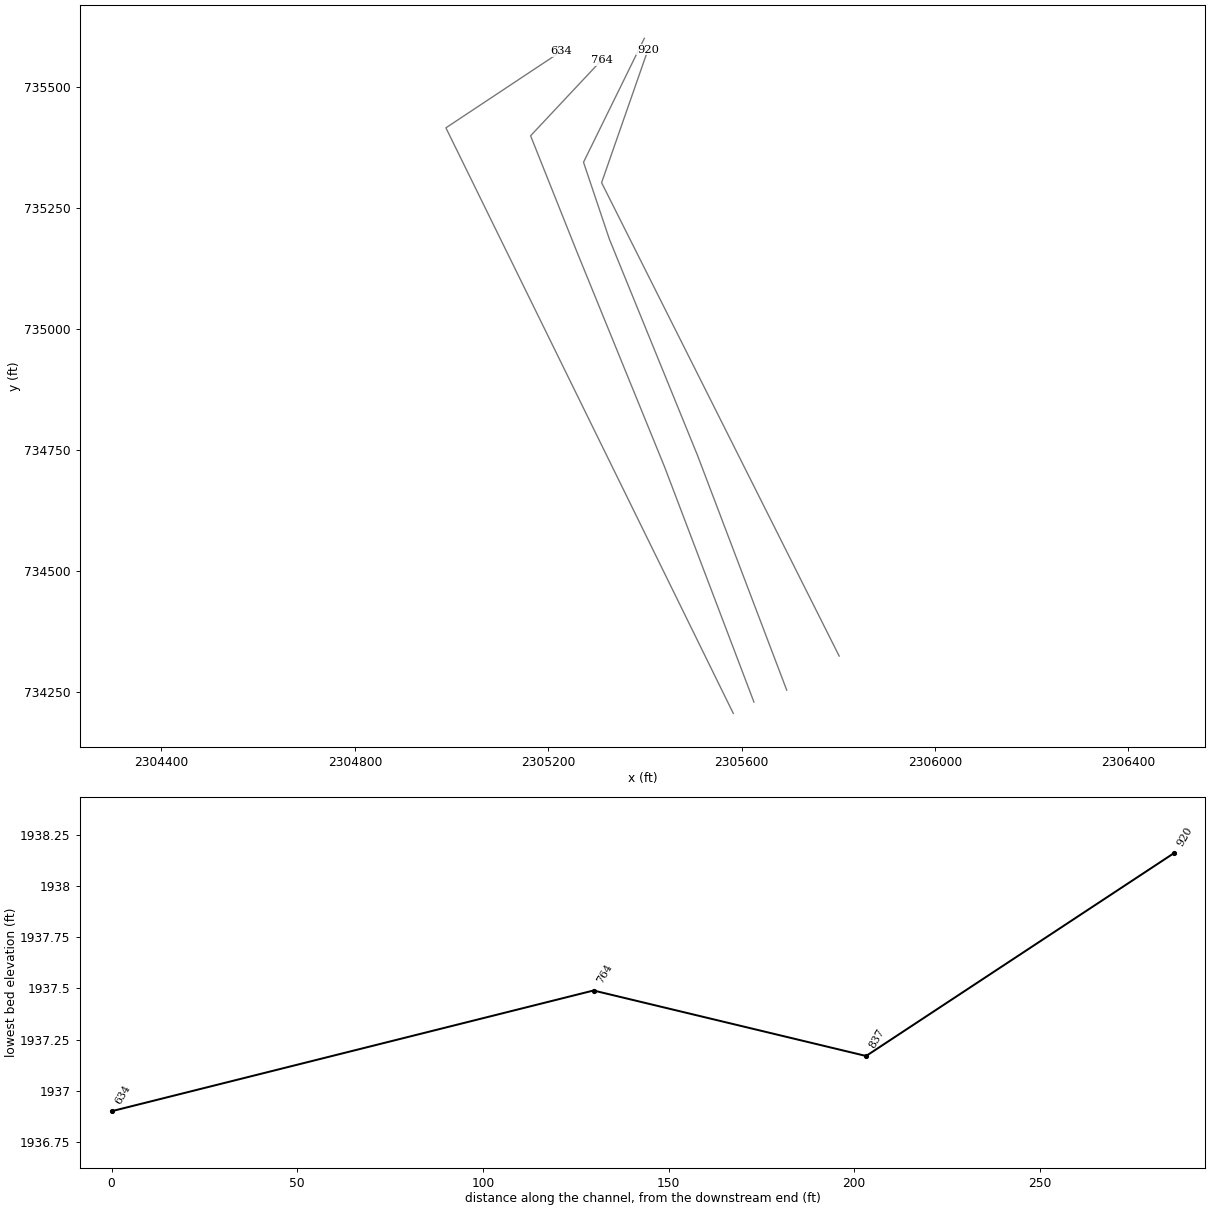
HEC-RAS study LAZYRN.prj: LAZYRN

--- LAZYRN.g01 (geometry) --- (continued)

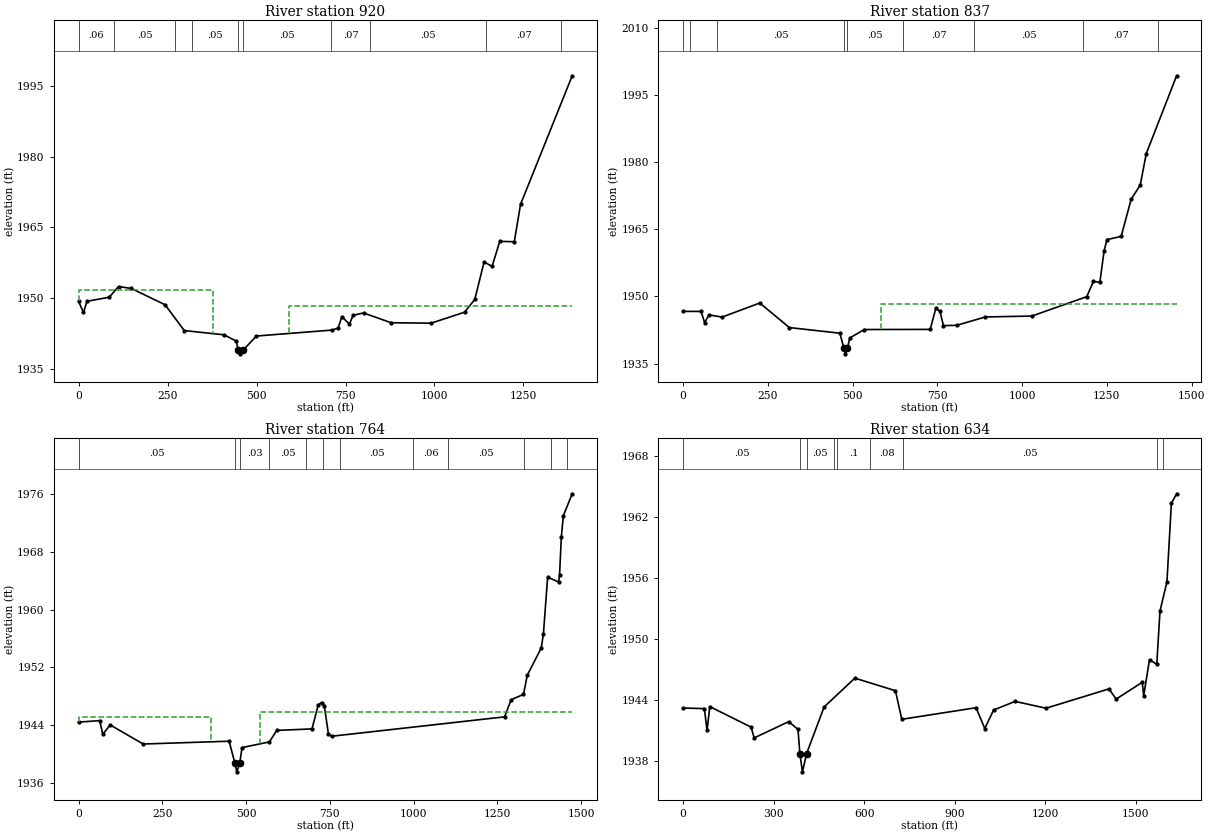
Type RM Length L Ch R = 1 ,920     ,82.8,82.8,81.3
BEGIN DESCRIPTION:
Structure XS 4 and 1
END DESCRIPTION:
XS GIS Cut Line= 3
2305801.63532575734323.9454048432305310.28920349735302.943317626
2305406.34182889735578.171032729
#Sta/Elev= 30
       0  1949.3    13.9 1946.94    23.8 1949.31    86.4 1950.18   112.3 1952.45
     148 1952.04   243.1 1948.58     297  1943.1   408.7  1942.2     443 1940.87
  448.661938.905   453.4 1938.16  463.161938.991   499.7 1941.94     713 1943.21
   729.1 1943.62   739.8 1946.04   761.2 1944.47   771.2 1946.34   800.6 1946.84
   878.1 1944.76   990.5 1944.67  1084.5    1947  1113.2 1949.72  1139.4 1957.66
  1161.8 1956.72  1183.4 1962.03  1224.2 1961.96  1241.8  1969.9  1386.9 1997.18
#Mann= 10, -1 ,  0
       0    0.06       0     100    0.05       0     270    0.06       0
     320    0.05       0  448.66   0.045       0  463.16    0.05       0
     710    0.07       0     820    0.05       0 1145.38    0.07       0
 1355.38    0.05       0
#XS Ineff= 2 , 0
          376.88 1951.78  591.21         1948.22
Permanent Ineff=
       F       F
Bank Sta=448.66,463.16
XS Rating Curve= 0 ,0
Exp/Cntr(USF)=0,0
Exp/Cntr=0.3,0.1

Type RM Length L Ch R = 1 ,837     ,73.3,73.4,72.9
BEGIN DESCRIPTION:
Structure XS 3
END DESCRIPTION:
XS GIS Cut Line= 5
2305693.19659438734253.3503277282305508.61218078734739.098784561
2305326.45650947735185.9873648482305272.91953826735345.233170706
2305398.69392232 735601.50071411
#Sta/Elev= 30
       0 1946.66    53.4 1946.64      64 1944.13    76.8 1945.87   115.4 1945.38
   226.6 1948.52   313.8 1943.04   462.7 1941.78   474.8 1938.39   479.1 1937.17
  484.98  1938.4   491.9 1940.72   534.8  1942.6   729.2 1942.63   745.6 1947.33
   757.9 1946.64   768.1 1943.48     807 1943.53   891.7 1945.41  1028.7 1945.61
  1190.6 1949.93  1210.3 1953.34  1229.4 1953.15  1241.7 1960.11  1250.3 1962.69
  1292.2  1963.4  1321.7 1971.71  1348.4 1974.85  1366.2 1981.89  1455.7 1999.28
#Mann= 9, -1 ,  0
       0    0.05       0      20    0.06       0     100    0.05       0
   474.8   0.045       0  484.98    0.05       0  649.64    0.07       0
  859.64    0.05       0 1180.23    0.07       0 1400.23    0.05       0
#XS Ineff= 2 , 0
                          584.09         1948.28
Permanent Ineff=
       F       F
Bank Sta=474.8,484.98
XS Rating Curve= 0 ,0
Exp/Cntr(USF)=0,0
Exp/Cntr=0.3,0.1

Type RM Length L Ch R = 1 ,764     ,126.9,129.8,122.1
BEGIN DESCRIPTION:
Structure XS 2
END DESCRIPTION:
XS GIS Cut Line= 5
2305625.33063183734228.8884582912305440.74621823734714.636915124
2305258.59054692735161.5254954112305163.45785688735399.964011392
2305310.30389451735556.514779416
#Sta/Elev= 30
       0 1944.39    63.1  1944.6    72.4 1942.71    94.5    1944   192.9 1941.35
   449.6 1941.74   466.7 1938.68   472.4 1937.49  481.021938.659   488.1 1940.86
   569.9 1941.64   591.5 1943.24   696.9 1943.45   715.4 1946.78   725.4 1947.11
   733.8 1946.61     746  1942.7   755.6 1942.43  1271.6 1945.12  1291.4  1947.5
  1328.2 1948.24  1339.5  1950.9  1381.3 1954.69  1387.7 1956.67  1400.3 1964.51
  1432.9 1963.84  1435.8  1964.8  1441.2 1970.11  1447.1 1973.03  1473.6 1976.08
#Mann= 12, -1 ,  0
       0    0.05       0   466.7   0.045       0  481.02    0.03       0
  569.64    0.05       0  679.64    0.07       0  729.64    0.06       0
  779.64    0.05       0  999.64    0.06       0 1102.22    0.05       0
 1328.94    0.06       0 1408.94    0.07       0 1458.94    0.05       0
#XS Ineff= 2 , 0
          396.24 1945.07  541.15         1945.86
Permanent Ineff=
       F       F
Bank Sta=466.7,481.02
XS Rating Curve= 0 ,0
Exp/Cntr(USF)=0,0
Exp/Cntr=0.3,0.1

Type RM Length L Ch R = 1 ,634     ,,,
BEGIN DESCRIPTION:
Structure XS 1
END DESCRIPTION:
XS GIS Cut Line= 3
 2305582.6309476734205.4165524762304988.31916669735416.383263598
2305227.00164779735574.728991785
#Sta/Elev= 30
       0 1943.18      71 1943.12    79.9 1940.98    88.9 1943.32   225.8  1941.3
   235.9 1940.24   350.6 1941.84   381.2 1941.07387.38771938.656     396  1936.9
  409.421938.678   467.6 1943.28   569.5 1946.12     704 1944.88     725 1942.07
   971.1 1943.21   999.9 1941.16    1029 1942.98  1100.3 1943.83  1202.8 1943.16
  1411.2 1945.06  1435.2 1944.06  1521.6 1945.71  1526.4  1944.4  1545.6 1947.94
  1569.6 1947.48  1580.3 1952.72  1603.4 1955.61  1618.1 1963.33  1635.4 1964.26
#Mann= 9, -1 ,  0
       0    0.05       0387.3877   0.045       0  409.42    0.05       0
     500    0.03       0     510     0.1       0     620    0.08       0
     730    0.05       0 1568.94    0.06       0 1588.94    0.07       0
Bank Sta=387.3877,409.42
XS Rating Curve= 0 ,0
Exp/Cntr(USF)=0,0
Exp/Cntr=0.3,0.1
LCMann Table=0

Chan Stop Cuts=-1
Use User Specified Reach Order=0
Composite Channel Slope=5